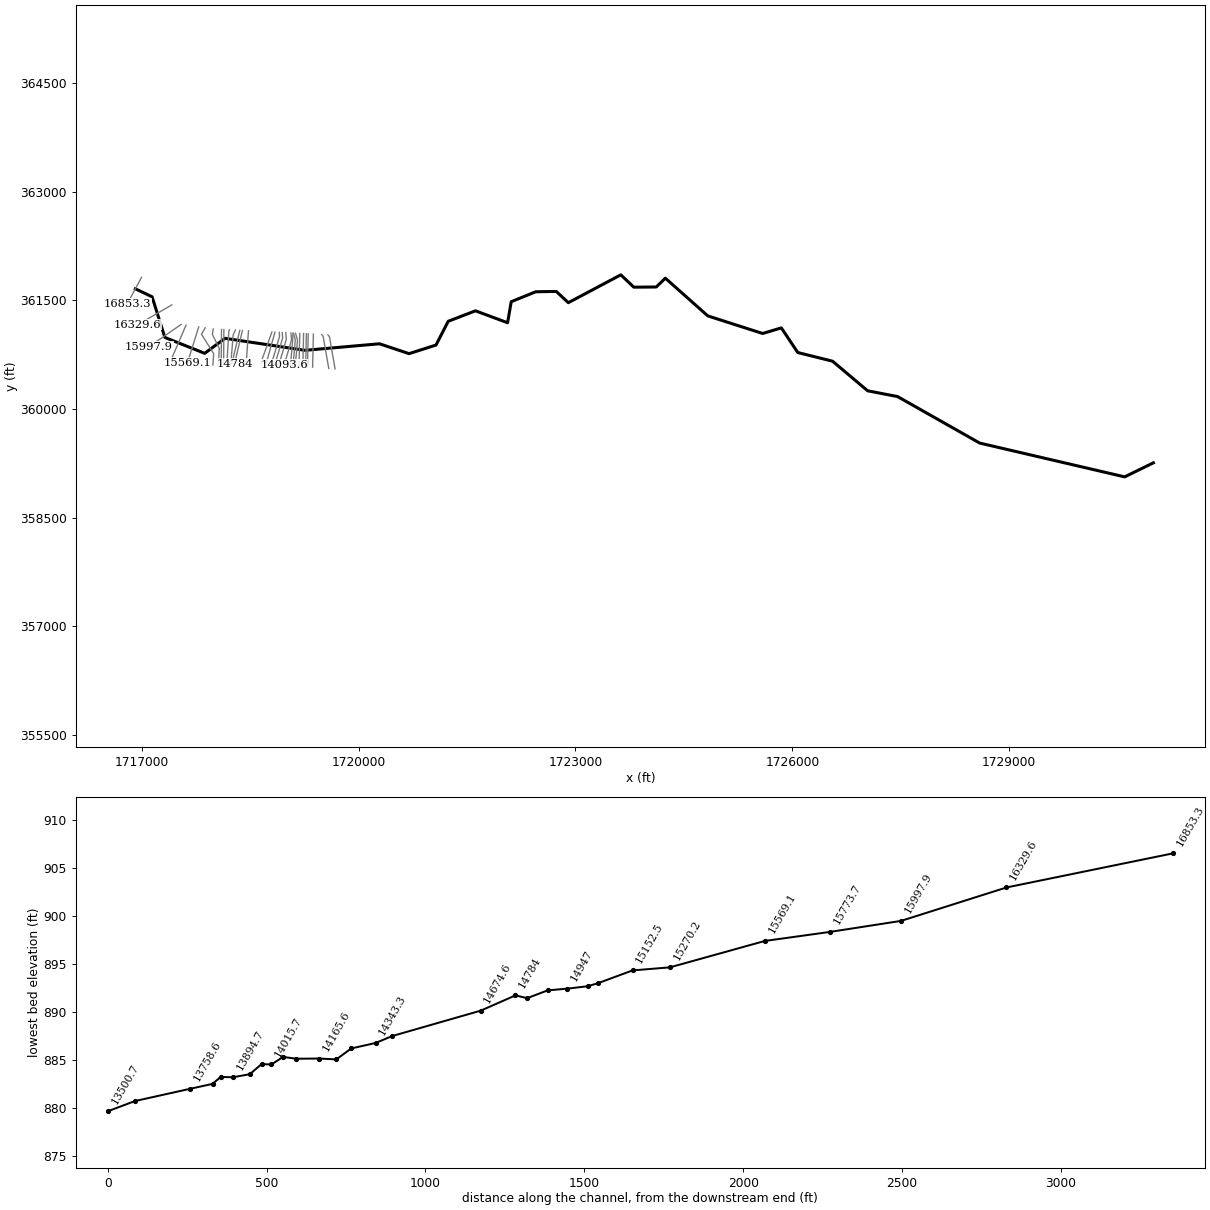
--- SIXMILECK.prj (project) ---

Proj Title=SIXMILECK
Current Plan=p01
Default Exp/Contr=0,0
English Units
Geom File=g01
Flow File=f01
Plan File=p01
BEGIN DESCRIPTION:
END DESCRIPTION:
DSS Export Rating Curves= 0
DSS Export Rating Curve Sorted= 0
DSS Export Volume Flow Curves= 0
DXF OffsetX= 0
DXF OffsetY= 0
DXF ScaleX= 0
DXF ScaleY= 0

--- SIXMILECK.p01 (plan) ---

Plan Title=Floodplain
Program Version=4.00
Geom File=g01
Flow File=f01
K Sum by GR=0
Std Step Tol=0.01
Critical Tol=0.01
Num of Std Step Trials=20
Max Error Tol=0.3
Flow Tol Ratio=0.001
Split Flow NTrial=30
Split Flow Tol=0.02
Split Flow Ratio=0.02
Log Output Level=0
Friction Slope Method=1
Unsteady Friction Slope Method=2
Unsteady Bridges Friction Slope Method=1
Global Log Level=0
CheckData=False
Run HTab=0
Run UNet=0
Run PostProcess=0
UNET Theta=0
UNET Theta Warmup=0
UNET ZTol=0
UNET ZSATol=0
UNET MxIter=0
UNET MaxInSteps=0
UNET DtIC=0
UNET DtMin=0
UNET MaxCRTS=0
UNET WFStab=0
UNET SFStab=0
UNET WFX=0
UNET SFX=0
UNET DSS MLevel=0
UNET DZMax Abort=0
UNET Convert EG Bridges=0
UNET Use Existing IB Tables=0
UNET Froude Limit=0
UNET Froude Power=0
Write IC File=0
Echo Input=False
Echo Output=False
Write Detailed=0

--- SIXMILECK.f01 (steady flow) ---

Flow Title=NFF Regression Equation
Program Version=4.00
Number of Profiles=1
Profile Names=P100yr
River Rch & RM=SIXMILECK,Main      ,16853.3
895.2638
River Rch & RM=SIXMILECK,Main      ,15997.9
968.1374
River Rch & RM=SIXMILECK,Main      ,14093.6
1072.354
River Rch & RM=SIXMILECK,Main      ,11575.2
1175.636
River Rch & RM=SIXMILECK,Main      ,7787.2
1294.295
River Rch & RM=SIXMILECK,Main      ,3851.5
1410.483
River Rch & RM=SIXMILECK,Main      ,364.9
1566.124
River Rch & RM=SIXMILECK,Main      ,215.1
1567.267
Boundary for River Rch & Prof#=SIXMILECK,Main      ,1
Up Type=0
Dn Type=3
Dn Slope=0.016211

--- SIXMILECK.g01 (geometry) ---

Geom Title=USGS 10m DEM
Program Version=4.10

River Reach=SIXMILECK       ,Main
Reach XY= 30
     1716913.365      361660.321     1717144.419      361550.548
     1717321.472      360988.493     1717872.108      360768.947
     1718153.623      360976.099     1719260.205      360810.554
      1720289.77      360900.852     1720698.763      360764.521
      1721071.46      360883.146      1721240.25      361211.515
     1721616.986       361356.48     1722061.431       361191.55
     1722111.778      361482.348     1722451.188      361619.675
     1722735.042      361624.015     1722901.709      361468.633
     1723627.354      361853.558      1723807.09      361683.043
     1724117.854      361685.647     1724243.722      361807.175
     1724830.528      361286.168     1725589.209      361043.112
     1725847.889      361120.369      1726075.32      360779.918
     1726556.223      360660.126     1727041.465      360251.098
     1727455.528      360171.237     1728590.945      359528.876
     1730596.153      359061.688     1730993.723      359256.133

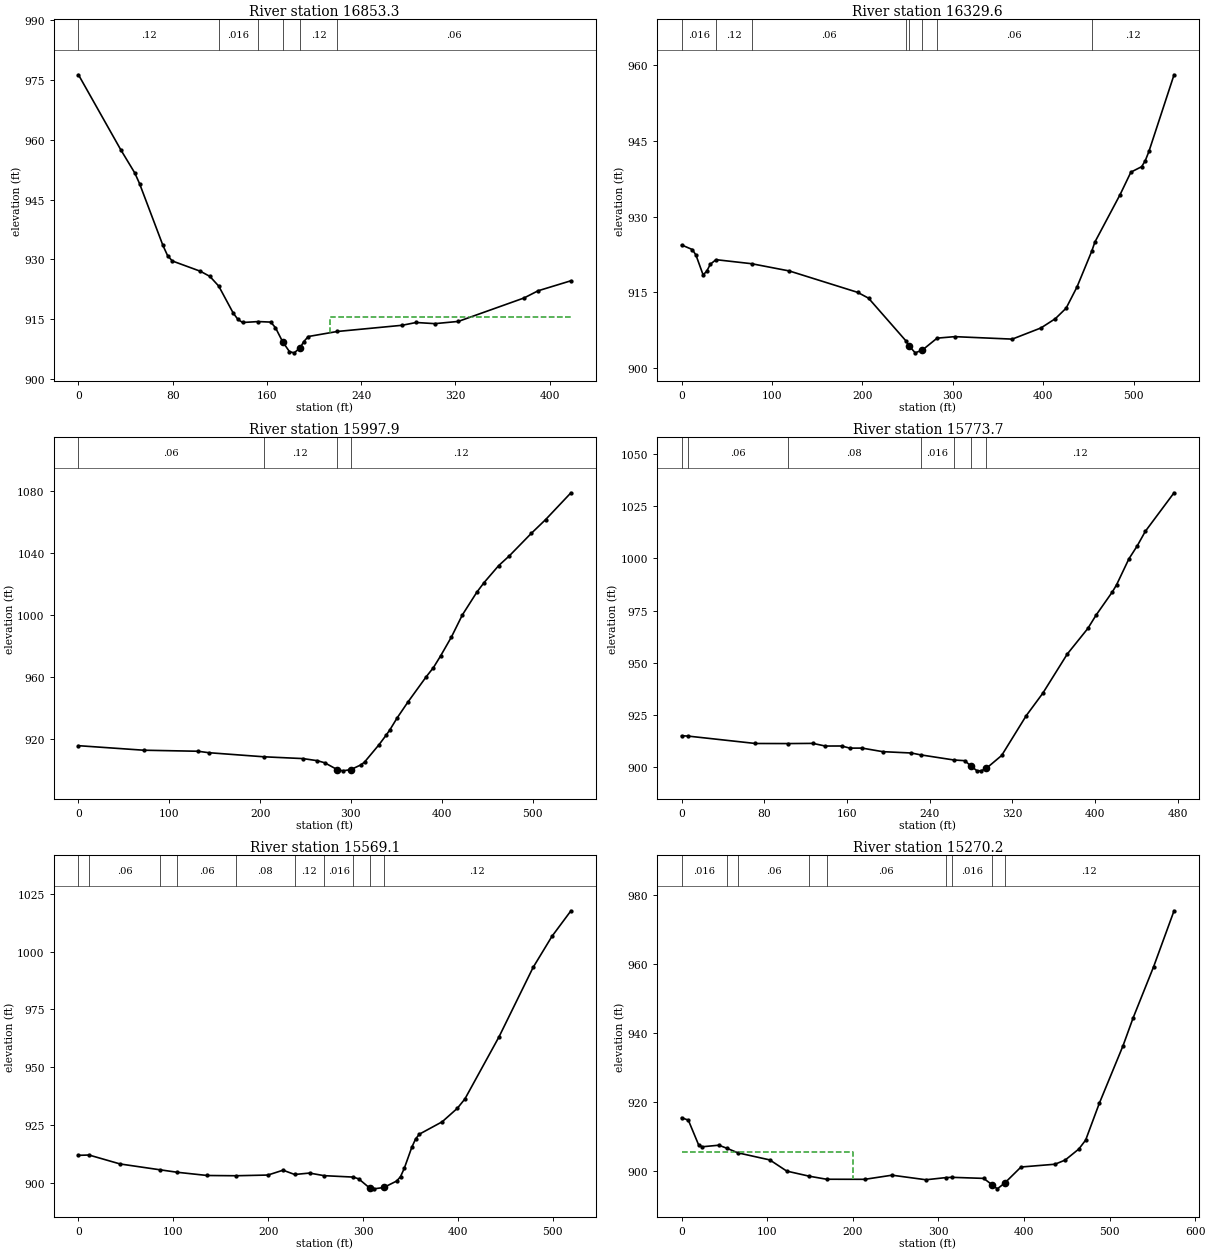
Type RM Length L Ch R = 1 ,16853.3 ,535.9,523.7,510.6
XS GIS Cut Line= 2
     1716999.025       361819.42     1716800.877      361451.395
#Sta/Elev= 30
       0  976.36    35.8  957.58    47.8   951.7    51.8  949.06    71.6  933.57
    75.6  930.97    79.6  929.61   103.5  927.02   111.5  925.74  119.03923.3062
   131.4  916.49   135.4  914.92   139.3  914.16  152.57914.3893   163.2  914.26
   167.2  912.86   173.2  909.37   179.1  906.83   183.1  906.54   188.2  907.82
   191.1  909.32   195.1  910.64  219.66911.9038   274.7  913.46   286.6  914.16
   302.5  913.87   322.4  914.43   378.2  920.32   390.1  922.12     418  924.64
#Mann= 6 ,-1 , 0
       0     .12       0  119.03    .016       0  152.57     .12       0
   173.2    .045       0   188.2     .12       0  219.66     .06       0
#XS Ineff= 2 , 0
                          213.48          915.61
Permanent Ineff=
       F       F
Bank Sta=173.2,188.2
XS Rating Curve= 0 ,0
Exp/Cntr=0.3,0.1

Type RM Length L Ch R = 1 ,16329.6 ,329.9,331.7,333.4
XS GIS Cut Line= 2
      1717417.41      361438.398     1716946.839      361164.503
#Sta/Elev= 30
       0  924.38    11.9  923.47    15.9  922.37    23.8  918.45    27.8  919.16
    31.8  920.56   38.07921.4615   77.46920.6616   119.2  919.22   194.7  914.98
   206.7  913.83  248.34905.3046   251.3  904.42   258.3  902.99   266.3  903.55
  282.51905.9016     302   906.2   365.6  905.71   397.4  907.93   413.3  909.77
   425.2  911.85   437.2  916.05  453.38 923.085     457  924.96   484.9  934.38
   496.8  938.82   508.7   939.9   512.7   941.1   516.7  942.91   544.5  958.12
#Mann= 8 ,-1 , 0
       0    .016       0   38.07     .12       0   77.46     .06       0
  248.34     .12       0   251.3    .045       0   266.3     .12       0
  282.51     .06       0  453.38     .12       0
Bank Sta=251.3,266.3
XS Rating Curve= 0 ,0
Exp/Cntr=0.3,0.1

Type RM Length L Ch R = 1 ,15997.9 ,211.5,224.2,236.9
XS GIS Cut Line= 2
     1717548.046      361168.459     1717101.172      360861.158
#Sta/Elev= 30
       0  915.73    71.8  912.81   131.6  912.14   143.6   911.2  203.96 908.576
   247.2  907.41   263.2  906.04   271.2  904.69   284.8  900.35   291.1  899.51
   299.8  900.29     311  903.36     315  905.16     331  916.41     339  922.68
     343  926.04   350.9  933.64   362.9  943.98   382.8  960.08   390.8  966.03
   398.8  973.66   410.7  985.84   422.7 1000.03   438.7 1014.75   446.6 1020.88
   462.6 1031.79   474.6 1038.23   498.5 1052.57   514.4 1061.53   542.3 1078.82
#Mann= 4 ,-1 , 0
       0     .06       0  203.96     .12       0   284.8    .045       0
   299.8     .12       0
Bank Sta=284.8,299.8
XS Rating Curve= 0 ,0
Exp/Cntr=0.3,0.1

Type RM Length L Ch R = 1 ,15773.7 ,202,204.6,206.6
XS GIS Cut Line= 2
     1717614.406      361159.133     1717425.938      360721.506
#Sta/Elev= 30
       0  915.15    6.22914.9917    71.5  911.45  102.69911.4095   127.1   911.5
     139  910.23   154.9  910.25   162.8  909.23   174.7  909.24   194.6  907.54
   222.4  906.89  231.32906.0059  263.47903.5543     274  903.22   279.9  900.69
   285.9  898.36   289.9   898.4   294.9  899.56   309.7  905.71   333.5  924.77
   349.4  935.42   373.2  954.26   393.1  966.51     401  972.83   416.9  984.06
   420.9   987.4   432.8   999.8   440.8 1005.95   448.7 1012.97   476.5 1031.43
#Mann= 7 ,-1 , 0
       0     .08       0    6.22     .06       0  102.69     .08       0
  231.32    .016       0  263.47     .08       0   279.9    .045       0
   294.9     .12       0
Bank Sta=279.9,294.9
XS Rating Curve= 0 ,0
Exp/Cntr=0.3,0.1

Type RM Length L Ch R = 1 ,15569.1 ,278.8,298.9,318.6
XS GIS Cut Line= 2
     1717789.779      361134.486     1717634.069      360639.386
#Sta/Elev= 30
       0  911.91   11.12912.0386    43.9  908.17   86.12905.6414     104904.5865
   135.7  903.19  165.92903.0789   199.6  903.38   215.6  905.48  227.84 903.622
   243.5  904.24  258.81903.1172  289.77902.4963   295.4  901.71   306.7  897.83
   311.4  897.42   321.7     898   335.4  900.81   339.4   902.7   343.3  906.24
   351.3  915.42   355.3  919.01   359.3  921.07   383.3  926.41   399.2  932.22
   407.2  936.26   443.2  963.15   479.1  993.14     499  1006.6     519 1017.64
#Mann= 10 ,-1 , 0
       0    .016       0   11.12     .06       0   86.12     .08       0
     104     .06       0  165.92     .08       0  227.84     .12       0
  258.81    .016       0  289.77     .12       0   306.7    .045       0
   321.7     .12       0
Bank Sta=306.7,321.7
XS Rating Curve= 0 ,0
Exp/Cntr=0.3,0.1

Type RM Length L Ch R = 1 ,15270.2 ,119.7,117.7,114.9
XS GIS Cut Line= 4
     1717879.046       361121.94     1717828.025      361032.394
     1717996.642       360763.52     1717985.981      360608.937
#Sta/Elev= 30
       0  915.36     7.9  914.65    19.8  907.53    23.8   906.9    43.6  907.36
   53.53906.4111   65.76905.1474   103.1  903.08   122.9  899.83  149.21898.3447
  169.39897.4616   214.1  897.44   245.9  898.64   285.6  897.31  308.84897.9406
  315.97898.0166     353  897.71   362.4  895.93   368.9  894.67   377.4  896.32
   396.6  901.02   436.3  901.83   448.2  903.04   464.1  906.24   472.1  908.84
     488   919.5   515.8   936.3   527.7  944.47   551.5  959.26   575.4  975.55
#Mann= 9 ,-1 , 0
       0    .016       0   53.53     .08       0   65.76     .06       0
  149.21     .08       0  169.39     .06       0  308.84     .12       0
  315.97    .016       0   362.4    .045       0   377.4     .12       0
#XS Ineff= 2 , 0
          200.25  905.38
Permanent Ineff=
       F       F
Bank Sta=362.4,377.4
XS Rating Curve= 0 ,0
Exp/Cntr=0.3,0.1

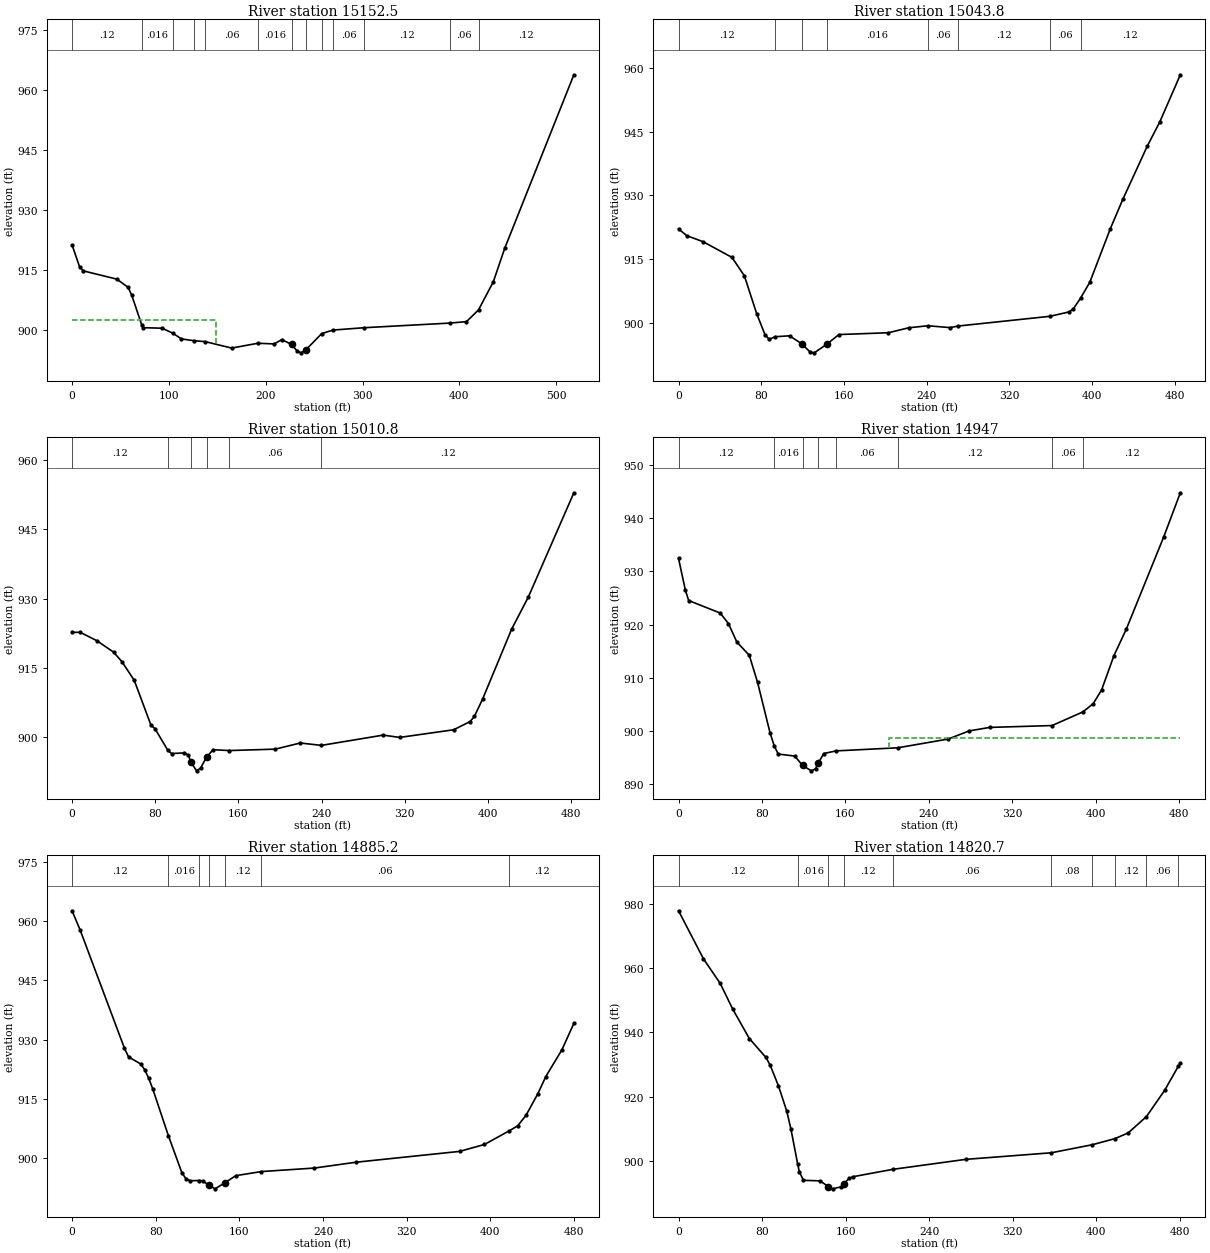
Type RM Length L Ch R = 1 ,15152.5 ,119.5,108.7,59.4
XS GIS Cut Line= 4
     1717990.295      361106.305     1717978.413      361030.186
     1718074.767      360837.478     1718060.495      360612.114
#Sta/Elev= 30
       0  921.27     7.7  915.87    11.6  914.81    46.2  912.75    57.8  910.72
    61.6  908.76    71.9901.3567    73.2  900.63      93   900.5  104.38 899.213
     113  897.82   125.8  897.38   137.4 897.155   164.8  895.54  191.84 896.738
   208.7  896.58   216.7  897.65   226.7  896.44   232.6  894.77   236.6  894.35
   241.7  895.15  257.88 899.156  269.49900.0345  301.47 900.619  390.26901.7781
   407.4  902.14  419.85905.0745   435.1  912.09     447  920.52   518.3  963.76
#Mann= 13 ,-1 , 0
       0     .12       0    71.9    .016       0  104.38     .12       0
   125.8     .08       0   137.4     .06       0  191.84    .016       0
   226.7    .045       0   241.7     .12       0  257.88    .016       0
  269.49     .06       0  301.47     .12       0  390.26     .06       0
  419.85     .12       0
#XS Ineff= 2 , 0
          148.31  902.65
Permanent Ineff=
       F       F
Bank Sta=226.7,241.7
XS Rating Curve= 0 ,0
Exp/Cntr=0.3,0.1

Type RM Length L Ch R = 1 ,15043.8 ,32.7,33,71.3
XS GIS Cut Line= 2
     1718104.805       361099.32     1718101.111      360613.846
#Sta/Elev= 30
       0  922.12       8  920.55    23.9  919.11    51.7  915.44    63.7  911.12
    75.6  902.23    83.6  897.32    87.6  896.21    93.6  896.81   107.4  897.02
   119.4  895.11   127.3   893.2   131.3  893.02   143.3  895.02   155.2  897.32
     203  897.74   222.8  898.91  241.28899.3826   262.6  898.95  270.81899.3242
  359.42 901.605     378  902.64     382  903.35  388.96905.8654   397.9  909.59
   417.8  922.19   429.8  929.05   453.6  941.62   465.6  947.25   485.5  958.34
#Mann= 8 ,-1 , 0
       0     .12       0    93.6    .016       0   119.4    .045       0
   143.3    .016       0  241.28     .06       0  270.81     .12       0
  359.42     .06       0  388.96     .12       0
Bank Sta=119.4,143.3
XS Rating Curve= 0 ,0
Exp/Cntr=0.3,0.1

Type RM Length L Ch R = 1 ,15010.8 ,65,63.8,62.6
XS GIS Cut Line= 2
     1718137.537      361097.865     1718133.864      360615.242
#Sta/Elev= 30
       0  922.73       8   922.7    23.9  920.89    39.9  918.42    47.9  916.37
    59.8  912.31    75.8  902.64    79.8  901.81   92.14897.1353    95.7  896.45
   107.7  896.58   111.7  896.12   114.3  894.61   119.7   892.7   123.6   893.3
   129.3  895.65   135.6  897.28  151.21 897.097   195.4   897.4   219.4  898.73
  239.82898.2173   299.2  900.44   315.1  899.94     367   901.6   382.9  903.39
   386.9  904.48   394.9  908.28   422.8  923.42   438.8  930.35   482.6  952.95
#Mann= 6 ,-1 , 0
       0     .12       0   92.14    .016       0   114.3    .045       0
   129.3    .016       0  151.21     .06       0  239.82     .12       0
Bank Sta=114.3,129.3
XS Rating Curve= 0 ,0
Exp/Cntr=0.3,0.1

Type RM Length L Ch R = 1 ,14947   ,62.1,61.8,61.4
XS GIS Cut Line= 3
     1718216.225      361094.368     1718206.836      361081.224
     1718178.571      360617.148
#Sta/Elev= 30
       0  932.45     6.5  926.52     9.7  924.53      40  922.16    47.9  920.17
    55.9  916.71    67.8  914.22    75.8   909.1    87.7  899.64   91.79897.1145
    95.6  895.61   111.5  895.23   118.9  893.46   127.4  892.45   131.4  892.84
   133.9  893.92   139.3  895.71  150.97896.2067  210.15896.7906   258.6  898.44
   278.4  899.96   298.3  900.63   358.1 900.978  387.69903.5485   397.6  905.11
   405.6  907.68   417.5  914.17   429.4  919.18   465.2  936.52   481.1  944.82
#Mann= 8 ,-1 , 0
       0     .12       0   91.79    .016       0   118.9    .045       0
   133.9     .12       0  150.97     .06       0  210.15     .12       0
   358.1     .06       0  387.69     .12       0
#XS Ineff= 2 , 0
                          202.25          898.65
Permanent Ineff=
       F       F
Bank Sta=118.9,133.9
XS Rating Curve= 0 ,0
Exp/Cntr=0.3,0.1

Type RM Length L Ch R = 1 ,14885.2 ,68,64.5,61
XS GIS Cut Line= 4
     1718298.078       361090.33     1718265.928      361024.475
     1718237.302      360664.949     1718232.048      360619.428
#Sta/Elev= 30
       0   962.6     7.7  957.75    50.1  927.82      54  925.64    65.6  923.86
    69.4  922.42    73.3  920.24    77.2   917.5    92.1  905.72     105  896.33
     109  894.78   112.9  894.32  121.73894.3745   124.8  894.29   131.1  893.14
   136.7  892.27   146.1  893.79   156.5   895.6  180.98896.6385   231.8  897.53
   271.4     899   370.5  901.74   394.3  903.49  418.01906.9485     426  908.19
     434  910.84   445.4  916.35     453  920.68   468.3   927.4   479.8  934.11
#Mann= 7 ,-1 , 0
       0     .12       0    92.1    .016       0  121.73     .12       0
   131.1    .045       0   146.1     .12       0  180.98     .06       0
  418.01     .12       0
Bank Sta=131.1,146.1
XS Rating Curve= 0 ,0
Exp/Cntr=0.3,0.1

Type RM Length L Ch R = 1 ,14820.7 ,36.9,36.7,36.9
XS GIS Cut Line= 3
     1718357.134      361087.264     1718253.527      360648.926
     1718245.599      360620.006
#Sta/Elev= 30
       0  977.75    23.9  962.81    39.9  955.22    51.8  947.28    67.8   938.1
    83.7  932.22    87.7  929.85    95.7  923.39   103.6  915.59   107.6  910.02
  114.14899.0265   115.6   896.8   119.6   894.1   135.5  893.94   143.3  892.18
   147.5  891.46   155.4  892.06   158.3  893.09   163.4  894.73   167.4  895.25
  205.19897.5134     275  900.61  356.93 902.652  396.08905.1439  417.63907.0256
   430.5  908.81  447.98913.8946   465.4  922.03  478.58929.5573   480.4  930.52
#Mann= 10 ,-1 , 0
       0     .12       0  114.14    .016       0   143.3    .045       0
   158.3     .12       0  205.19     .06       0  356.93     .08       0
  396.08     .06       0  417.63     .12       0  447.98     .06       0
  478.58     .12       0
Bank Sta=143.3,158.3
XS Rating Curve= 0 ,0
Exp/Cntr=0.3,0.1

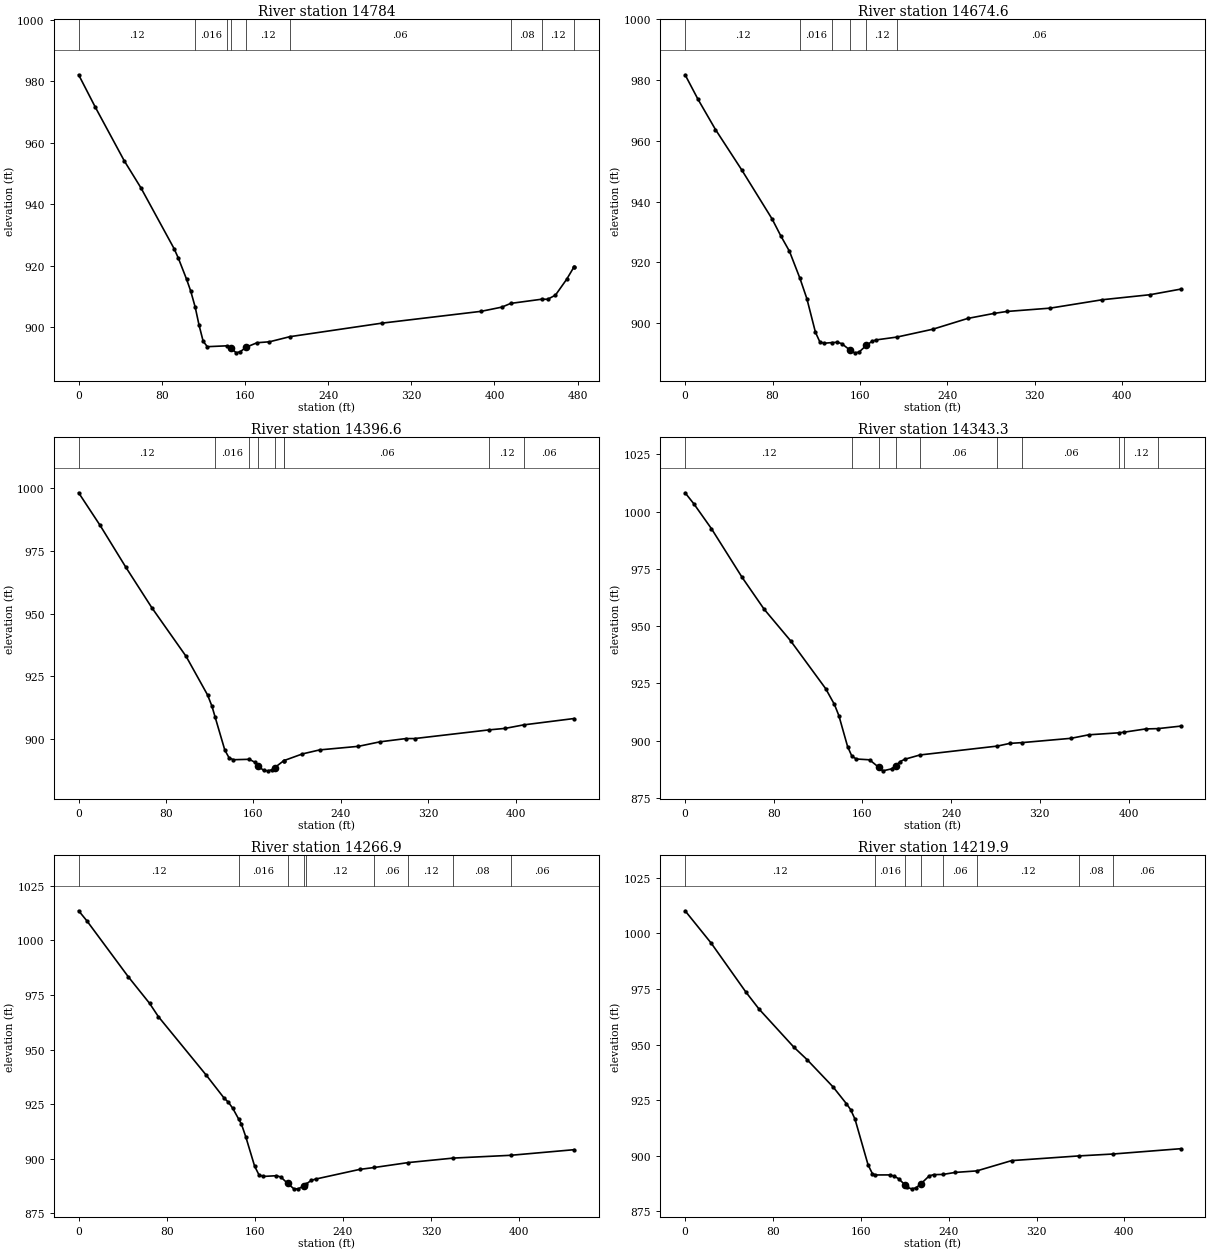
Type RM Length L Ch R = 1 ,14784   ,105.4,109.4,112.8
XS GIS Cut Line= 3
      1718394.07      361085.347     1718289.377      360642.416
     1718283.679       360621.63
#Sta/Elev= 30
       0  982.09      16  971.59    43.9  954.13    59.9  945.37    91.8  925.62
    95.8  922.62   103.8   915.7   107.8  911.84  112.17906.5545   115.8  900.81
   119.8   895.5   123.8  893.75  142.52894.0325   146.1  893.36   151.7  891.75
   155.7  892.17   161.1  893.58   171.7  895.04   183.6  895.34  203.22897.0025
   291.4  901.38   387.3  905.24   407.2  906.61  415.66907.8134  446.01909.1962
   451.1  909.14   458.7   910.5   469.5  915.66  476.55919.6692   476.7  919.76
#Mann= 9 ,-1 , 0
       0     .12       0  112.17    .016       0  142.52     .12       0
   146.1    .045       0   161.1     .12       0  203.22     .06       0
  415.66     .08       0  446.01     .12       0  476.55     .06       0
Bank Sta=146.1,161.1
XS Rating Curve= 0 ,0
Exp/Cntr=0.3,0.1

Type RM Length L Ch R = 1 ,14674.6 ,284.1,278,271.6
XS GIS Cut Line= 2
     1718478.025      361080.989     1718446.538      360628.573
#Sta/Elev= 30
       0  981.77    11.9  973.63    27.8  963.73    51.7   950.5    79.6  934.28
    87.5  928.75    95.5  923.63  105.07914.7383   111.4  908.05   119.3  896.92
   123.3  893.78   127.3  893.32  134.67893.5532   139.2  893.64   143.2  893.22
   150.9  891.07   155.2  890.16   159.1  890.38   165.9  892.62   171.1  893.96
     175  894.43  193.88895.3582   226.8  897.95   258.6  901.49   282.4  903.13
   294.4  903.79   334.2  904.89   381.9  907.66   425.7  909.32   453.5  911.15
#Mann= 6 ,-1 , 0
       0     .12       0  105.07    .016       0  134.67     .12       0
   150.9    .045       0   165.9     .12       0  193.88     .06       0
Bank Sta=150.9,165.9
XS Rating Curve= 0 ,0
Exp/Cntr=0.3,0.1

Type RM Length L Ch R = 1 ,14396.6 ,51.7,53.3,55
XS GIS Cut Line= 3
     1718802.012      361064.171     1718748.934      360915.987
     1718649.079      360637.209
#Sta/Elev= 30
       0  997.99    19.7     985    43.3  968.34    66.9  952.39    98.4  932.97
     118  917.66     122  913.21  124.85908.9716   133.8  895.74   137.7  892.69
   141.7  891.94  156.23 892.103   161.4  890.89   164.4  889.38   169.2  887.74
   173.2  887.52   177.1  887.97   179.4  888.77   187.6 891.508  188.06891.6138
   204.8  894.24   220.6  895.84   256.1  897.26   275.8  899.05   299.5  900.34
   307.4  900.34  375.83903.8041   390.4  904.39   407.2905.7746   453.5  908.31
#Mann= 9 ,-1 , 0
       0     .12       0  124.85    .016       0  156.23     .12       0
   164.4    .045       0   179.4     .12       0   187.6    .016       0
  188.06     .06       0  375.83     .12       0   407.2     .06       0
Bank Sta=164.4,179.4
XS Rating Curve= 0 ,0
Exp/Cntr=0.3,0.1

Type RM Length L Ch R = 1 ,14343.3 ,76.3,76.4,76.2
XS GIS Cut Line= 3
     1718844.085      361061.987     1718794.941      360886.473
     1718723.557      360631.528
#Sta/Elev= 30
       0 1008.22     7.9  1003.4    23.8  992.52    51.5  971.23    71.3  957.37
    95.1  943.63   126.8  922.69   134.7  915.78   138.7  910.92   146.6  897.36
  150.47893.1708   154.5  891.96   166.4  891.61   174.8  888.28   178.3  886.79
   186.2  887.64   189.8  889.04   194.1  890.86   198.1  891.84  211.81893.7189
  281.72897.6058   292.9  898.78  303.82899.1106   348.2     901     364  902.52
  391.27903.3985  395.83 903.655   415.4  905.09   426.5 905.226     447  906.32
#Mann= 10 ,-1 , 0
       0     .12       0  150.47    .016       0   174.8    .045       0
   189.8    .016       0  211.81     .06       0  281.72    .016       0
  303.82     .06       0  391.27    .016       0  395.83     .12       0
   426.5     .06       0
Bank Sta=174.8,189.8
XS Rating Curve= 0 ,0
Exp/Cntr=0.3,0.1

Type RM Length L Ch R = 1 ,14266.9 ,47,47,47.1
XS GIS Cut Line= 4
     1718902.857      361058.936     1718907.861       361006.66
     1718863.952      360849.841     1718794.856      360625.587
#Sta/Elev= 30
       0 1013.55     7.5 1008.94      45  983.39    64.4  971.18    72.4  965.09
   116.1  938.15     132  927.84   135.9  925.93   139.9  923.16  145.53917.9863
   147.8  915.92   151.8  910.03   159.8  896.62   163.7  892.68   167.7   891.9
   179.6  892.23   183.6  891.65   189.8   888.7   195.5  886.22   199.5  886.22
   204.8  887.69  206.87888.5339   211.4  890.13   215.4  890.71   255.1  895.11
  268.62 896.003  299.52898.2601   340.2900.3015  392.24901.5738     450  904.15
#Mann= 9 ,-1 , 0
       0     .12       0  145.53    .016       0   189.8    .045       0
   204.8    .016       0  206.87     .12       0  268.62     .06       0
  299.52     .12       0   340.2     .08       0  392.24     .06       0
Bank Sta=189.8,204.8
XS Rating Curve= 0 ,0
Exp/Cntr=0.3,0.1

Type RM Length L Ch R = 1 ,14219.9 ,54.4,54.3,54.4
XS GIS Cut Line= 4
     1718944.036      361056.799      1718950.83      360985.827
      1718906.92      360829.008     1718843.007      360621.574
#Sta/Elev= 30
       0  1010.2    23.8  995.61    55.4  973.59    67.3  965.99    99.1   948.8
     111  943.25   134.8   930.9   146.8  923.44   150.7  920.75   154.7  916.44
   166.6  895.88   170.6  891.83  173.35891.3281   186.5  891.35   190.5  890.75
   194.4  889.64     200  886.98   202.4   885.7   206.3  885.08   210.3  885.54
     215  887.48   222.2  890.88   226.2  891.46   234.7891.5598     246  892.47
   265.6893.1515   297.3  897.78  358.32899.8893  389.22 900.736   451.2  903.14
#Mann= 8 ,-1 , 0
       0     .12       0  173.35    .016       0     200    .045       0
     215     .12       0   234.7     .06       0   265.6     .12       0
  358.32     .08       0  389.22     .06       0
Bank Sta=200,215
XS Rating Curve= 0 ,0
Exp/Cntr=0.3,0.1

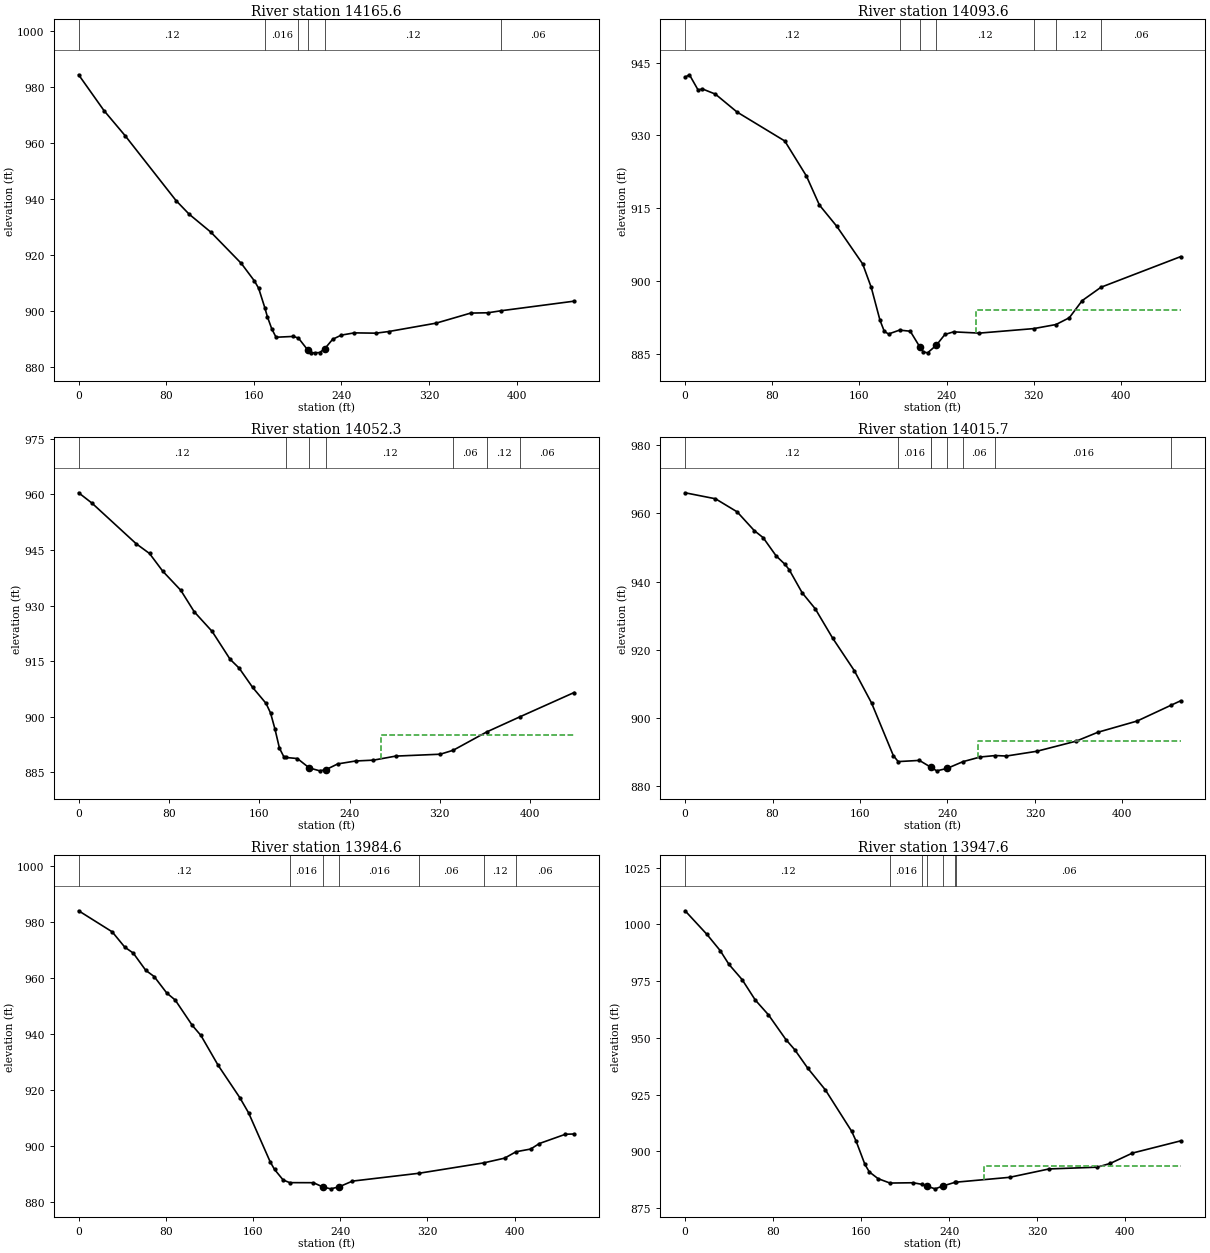
Type RM Length L Ch R = 1 ,14165.6 ,72.5,72,72.2
XS GIS Cut Line= 4
     1718993.046      361054.255     1719001.524      360965.688
     1718957.615      360808.869     1718898.482      360616.951
#Sta/Elev= 30
       0  984.27    23.2  971.49    42.6   962.5      89  939.42   100.9   934.6
   120.8  928.17   148.6  917.03   160.5  910.82   164.4   908.2  170.11901.1688
   172.4  898.02   176.4  893.72   180.3  890.73   196.2  891.02  200.79890.4116
   209.6  886.02   212.1  885.26   216.1  885.17     220  885.28   224.6  886.55
     232     890   239.9  891.48   251.8  892.29   271.5  892.18   283.3  892.77
   326.6  895.76   358.1  899.34   373.9  899.45  385.83 900.169   452.6  903.59
#Mann= 6 ,-1 , 0
       0     .12       0  170.11    .016       0  200.79     .12       0
   209.6    .045       0   224.6     .12       0  385.83     .06       0
Bank Sta=209.6,224.6
XS Rating Curve= 0 ,0
Exp/Cntr=0.3,0.1

Type RM Length L Ch R = 1 ,14093.6 ,36.1,41.3,45.3
XS GIS Cut Line= 4
      1719064.94      361050.523      1719073.66      360959.438
      1719029.75      360802.619     1718970.689      360610.934
#Sta/Elev= 30
       0  942.04       4  942.52    11.9  939.39    15.9   939.6    27.8  938.53
    47.7  934.83    91.5  928.86   111.4  921.62   123.3  915.64   139.2  911.27
     163   903.5   170.9  898.64   178.9  891.88   182.9  889.56   186.8  889.04
  196.83889.8381   206.7  889.61   215.6  886.32   218.6  885.35   222.6  885.15
   230.6  886.71   238.5  888.94   246.4  889.48   270.1  889.22  320.01890.1508
  340.43890.9866   352.7  892.39   364.5  895.92  381.82898.6876   454.9     905
#Mann= 7 ,-1 , 0
       0     .12       0  196.83    .016       0   215.6    .045       0
   230.6     .12       0  320.01     .06       0  340.43     .12       0
  381.82     .06       0
#XS Ineff= 2 , 0
                             267          893.93
Permanent Ineff=
       F       F
Bank Sta=215.6,230.6
XS Rating Curve= 0 ,0
Exp/Cntr=0.3,0.1

Type RM Length L Ch R = 1 ,14052.3 ,36.5,36.6,36.6
XS GIS Cut Line= 4
     1719093.055      361041.121     1719089.706      360970.547
      1719077.27      360808.172     1719056.286      360603.801
#Sta/Elev= 30
       0  960.45    11.8  957.66      51  946.68    62.8  944.05    74.6  939.24
    90.5  934.11   102.4  928.31   118.3  922.99   134.2  915.47   142.2  913.09
   154.1   907.9     166  903.57     170  900.99   173.9  896.66   177.9  891.47
   181.9  889.08  183.52888.9595   193.8  888.66   204.3  886.13   213.6  885.34
   219.3  885.69   229.5  887.21   245.4     888   261.2  888.23   280.9  889.32
   320.4  889.83  331.85890.9036  361.54895.8506  391.24 899.976     439   906.5
#Mann= 7 ,-1 , 0
       0     .12       0  183.52    .016       0   204.3    .045       0
   219.3     .12       0  331.85     .06       0  361.54     .12       0
  391.24     .06       0
#XS Ineff= 2 , 0
                          267.63          894.92
Permanent Ineff=
       F       F
Bank Sta=204.3,219.3
XS Rating Curve= 0 ,0
Exp/Cntr=0.3,0.1

Type RM Length L Ch R = 1 ,14015.7 ,31.1,31.2,31.2
XS GIS Cut Line= 4
     1719098.607      361048.775     1719124.862      360961.432
     1719112.426      360799.057     1719092.072      360600.818
#Sta/Elev= 30
       0  966.06    27.8   964.3    47.6  960.47    63.4  954.93    71.4  952.91
    83.3  947.55    91.2  945.14    95.2  943.52   107.1  936.74     119  932.08
   134.9  923.49   154.8  913.91   170.6  904.42   190.5  889.01  194.93887.2598
   214.3  887.61  224.54885.6541   224.6  885.64   230.2  884.55   239.6  885.25
  254.17887.2432     270  888.61  283.86889.0343   293.9  888.89   321.8  890.29
   357.7  893.25   377.6  895.86   413.5  899.15  444.19903.7355   453.3  905.08
#Mann= 8 ,-1 , 0
       0     .12       0  194.93    .016       0  224.54     .12       0
   224.6    .045       0   239.6     .12       0  254.17     .06       0
  283.86    .016       0  444.19     .12       0
#XS Ineff= 2 , 0
                          267.63          893.39
Permanent Ineff=
       F       F
Bank Sta=224.6,239.6
XS Rating Curve= 0 ,0
Exp/Cntr=0.3,0.1

Type RM Length L Ch R = 1 ,13984.6 ,35.8,36.9,38.2
XS GIS Cut Line= 4
     1719127.881      361047.256     1719155.597      360955.055
     1719143.161       360792.68     1719123.195      360598.225
#Sta/Elev= 30
       0  983.86    30.8  976.34    42.4  970.85    50.1  968.76    61.6  962.59
    69.3  960.38    80.9  954.48    88.6     952   104.2  942.98   112.2  939.34
     128  928.68   147.9  917.12   155.9  911.73   175.7  894.26   179.7  891.52
   187.6  887.76  193.61886.8035   215.4  886.78     224  885.26   231.3  884.59
     239  885.32   251.2  887.35  312.22890.1506   371.6 893.856   390.8  895.55
  401.29897.8348   414.7   898.8   422.7  900.77   446.6  904.08   454.6  904.17
#Mann= 7 ,-1 , 0
       0     .12       0  193.61    .016       0     224    .045       0
     239    .016       0  312.22     .06       0   371.6     .12       0
  401.29     .06       0
Bank Sta=224,239
XS Rating Curve= 0 ,0
Exp/Cntr=0.3,0.1

Type RM Length L Ch R = 1 ,13947.6 ,52.9,53,53
XS GIS Cut Line= 2
     1719187.416      361044.165     1719176.826      360593.756
#Sta/Elev= 30
       0 1005.96    19.9  995.54    31.9  988.43    39.9  982.34    51.8  975.69
    63.8  966.67    75.8  960.14    91.7  949.22    99.7  944.78   111.6   936.6
   127.6  927.05   151.5  908.82   155.5   904.5   163.5  894.26   167.5  890.98
   175.4  888.04  186.21886.0876   207.3  886.22  215.75885.4845   219.8  884.71
   227.3  883.54   234.8  884.86   245.3 886.406  246.62886.4852     295  888.61
   330.9   892.3   374.8  893.08   386.7  894.77   406.7  899.29   450.5  904.66
#Mann= 7 ,-1 , 0
       0     .12       0  186.21    .016       0  215.75     .08       0
   219.8    .045       0   234.8     .08       0   245.3     .12       0
  246.62     .06       0
#XS Ineff= 2 , 0
                          271.41          893.75
Permanent Ineff=
       F       F
Bank Sta=219.8,234.8
XS Rating Curve= 0 ,0
Exp/Cntr=0.3,0.1

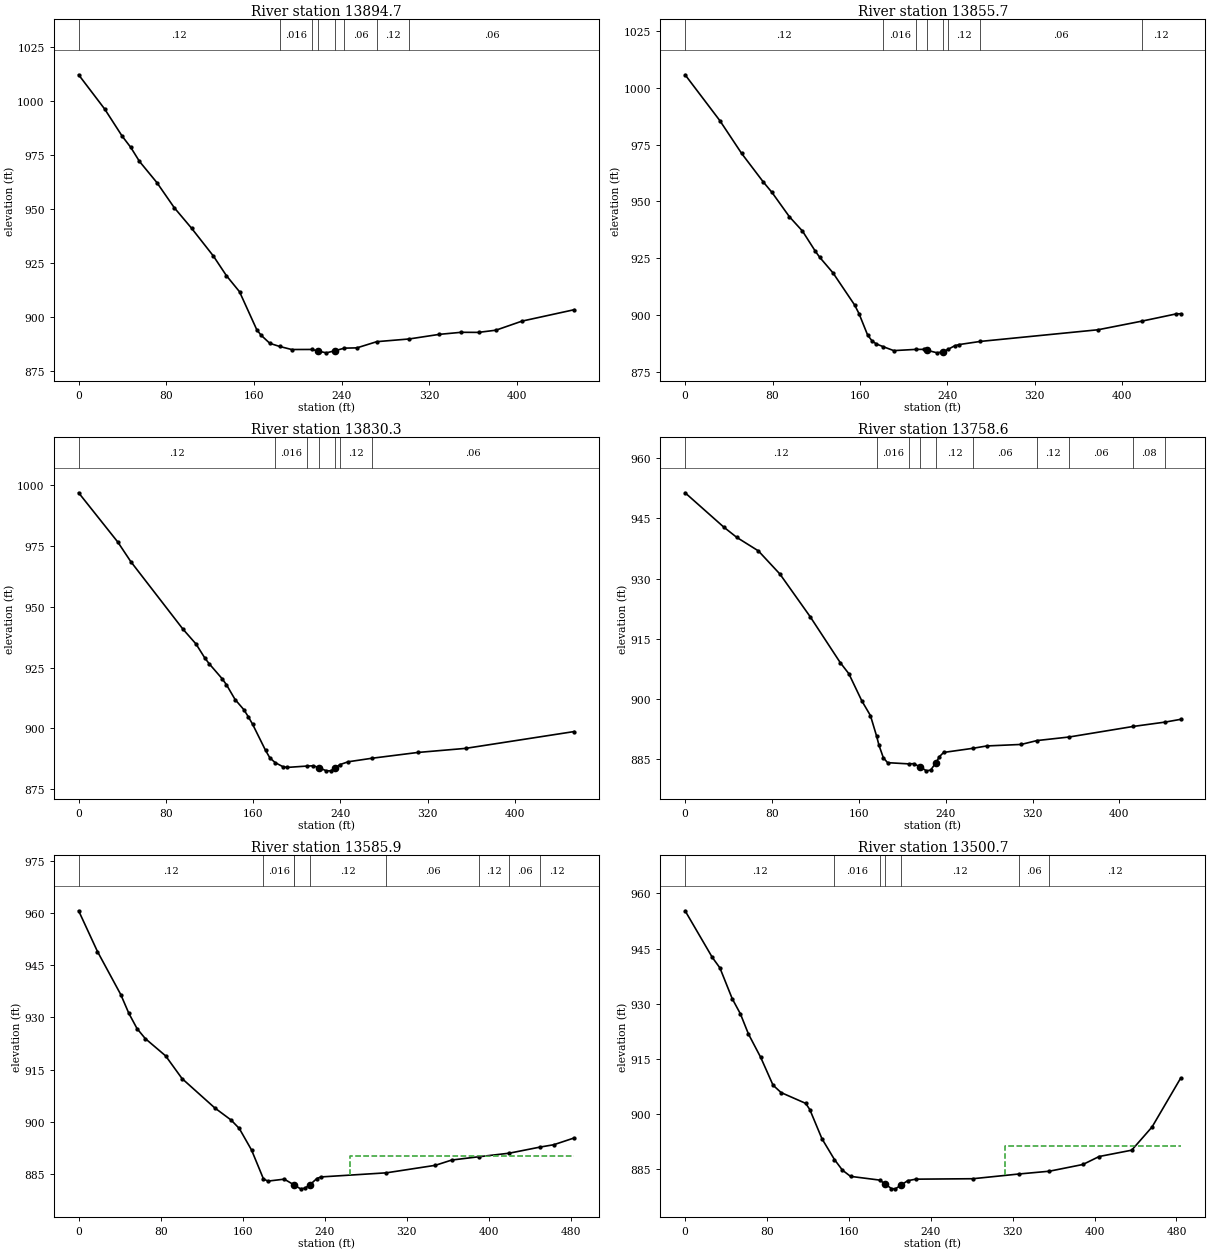
Type RM Length L Ch R = 1 ,13894.7 ,39,38.9,38.9
XS GIS Cut Line= 2
     1719240.158      361041.428     1719229.529      360589.364
#Sta/Elev= 30
       0 1011.98    23.8   996.1    39.7  983.58    47.6  978.34    55.5  971.88
    71.4  962.07    87.3  950.41   103.1   940.9     123  928.03   134.9  918.93
   146.8  911.53   162.6  893.88   166.6  891.33   174.5  887.61  183.47886.1734
   194.4  884.76  213.02884.7874   218.5  884.02   226.1  883.22   233.5  884.14
  242.56885.3986   253.9  885.52   272.1 888.394  301.65889.6477   329.2  891.78
   349.1  892.73   364.9  892.69   380.8  893.71   404.6  897.91   452.2  903.19
#Mann= 8 ,-1 , 0
       0     .12       0  183.47    .016       0  213.02     .08       0
   218.5    .045       0   233.5     .08       0  242.56     .06       0
   272.1     .12       0  301.65     .06       0
Bank Sta=218.5,233.5
XS Rating Curve= 0 ,0
Exp/Cntr=0.3,0.1

Type RM Length L Ch R = 1 ,13855.7 ,25.4,25.4,25.4
XS GIS Cut Line= 2
     1719278.696      361039.427     1719268.038      360586.155
#Sta/Elev= 30
       0 1005.81    31.8   985.6    51.7  971.16    71.6  958.53    79.5  953.96
    95.4  943.26   107.4  936.92   119.3  927.93   123.3  925.28   135.2  918.57
   155.1  904.35   159.1  900.56     167   891.1     171  888.53     175  887.17
  181.47885.9219   190.9  884.23  211.02884.7666   218.7  884.78   221.4  884.38
   230.7  883.25   236.4  883.83  240.56 884.759   246.6  886.36   250.6  886.89
   270.1888.2816   377.8  893.42  417.82897.2131   449.4  900.42   453.4  900.48
#Mann= 8 ,-1 , 0
       0     .12       0  181.47    .016       0  211.02     .08       0
   221.4    .045       0   236.4     .08       0  240.56     .12       0
   270.1     .06       0  417.82     .12       0
Bank Sta=221.4,236.4
XS Rating Curve= 0 ,0
Exp/Cntr=0.3,0.1

Type RM Length L Ch R = 1 ,13830.3 ,71.7,71.7,71.7
XS GIS Cut Line= 2
     1719304.065       361038.11     1719293.389      360584.042
#Sta/Elev= 30
       0  996.82    35.9  976.57    47.8  968.54    95.6  940.78   107.6  934.66
   115.5  929.03   119.5  926.64   131.5  920.42   135.5  917.92   143.4  911.85
   151.4  907.69   155.4  904.85   159.4  901.73   171.3  890.96   175.3  887.85
  180.16885.9044   187.3  884.22   191.2  883.94   209.7 884.505   215.1   884.6
   220.1  883.89   227.1  882.53   231.1  882.55   235.1   883.6  239.24885.0522
     247  886.25  268.79887.7017   310.8  890.08   354.6  891.76   454.2  898.68
#Mann= 7 ,-1 , 0
       0     .12       0  180.16    .016       0   209.7     .08       0
   220.1    .045       0   235.1     .08       0  239.24     .12       0
  268.79     .06       0
Bank Sta=220.1,235.1
XS Rating Curve= 0 ,0
Exp/Cntr=0.3,0.1

Type RM Length L Ch R = 1 ,13758.6 ,168.1,172.7,177.1
XS GIS Cut Line= 2
     1719375.654      361034.394     1719364.925      360578.081
#Sta/Elev= 30
       0  951.39    35.7  942.81    47.6  940.26    67.5  936.89    87.3  931.12
   115.1  920.51   142.9  909.01   150.8  906.25   162.7   899.5   170.7   895.8
  176.44890.6172   178.6  888.36   182.6  885.27   186.5  884.05  205.99883.7469
   210.4   883.8   216.1  883.05   222.3  882.01   226.2  882.21   231.1  884.07
   234.2  885.54   238.1   886.6  265.07887.6317   277.8  888.22   309.6   888.6
  324.16889.5663   353.7890.4525  412.78893.0892  442.33 894.181   456.4  894.86
#Mann= 10 ,-1 , 0
       0     .12       0  176.44    .016       0  205.99     .12       0
   216.1    .045       0   231.1     .12       0  265.07     .06       0
  324.16     .12       0   353.7     .06       0  412.78     .08       0
  442.33     .12       0
Bank Sta=216.1,231.1
XS Rating Curve= 0 ,0
Exp/Cntr=0.3,0.1

Type RM Length L Ch R = 1 ,13585.9 ,85.2,85.2,85.2
XS GIS Cut Line= 4
     1719489.818      361028.468     1719511.008      361003.037
     1719534.563      360865.473     1719588.539      360559.446
#Sta/Elev= 30
       0  960.62    18.4   948.9    41.1  936.55      49  931.15      57  926.76
      65  923.91    84.9  918.93   100.9  912.41   132.8  903.99   148.7  900.51
   156.7  898.09   168.7  891.88  180.26883.6159   184.6  882.96   200.6  883.52
  210.26881.8536   210.5  881.79   216.5  880.74   220.5  880.92   225.5  881.87
   232.4  883.71   236.4  884.16  300.23885.3412     348   887.5   363.9  889.01
   390.2 889.952  420.19890.9861  450.19892.7419   463.5  893.41   483.4  895.36
#Mann= 9 ,-1 , 0
       0     .12       0  180.26    .016       0  210.26     .12       0
   210.5    .045       0   225.5     .12       0  300.23     .06       0
   390.2     .12       0  420.19     .06       0  450.19     .12       0
#XS Ineff= 2 , 0
                          265.11           890.2
Permanent Ineff=
       F       F
Bank Sta=210.5,225.5
XS Rating Curve= 0 ,0
Exp/Cntr=0.3,0.1

Type RM Length L Ch R = 1 ,13500.7 ,39.4,39.4,39.4
XS GIS Cut Line= 4
     1719576.465      361023.971     1719598.248      360997.829
     1719621.803      360860.265     1719675.733      360554.494
#Sta/Elev= 30
       0  955.28    26.5  942.64      34  939.75      46   931.4      54  927.27
    61.9  921.77    73.9   915.4    85.9  907.87    93.8  905.85   117.8  902.92
   121.8  901.25   133.7   893.3  145.94887.6335   153.7  884.76   161.6  883.07
  189.98882.0608   195.7  880.97   201.5  879.75   205.4  879.68   210.7  880.64
   217.4  881.89   225.3  882.31   281.1  882.43  325.86883.7095  355.85 884.473
   388.6   886.3   404.5  888.47   436.3  890.19   456.2  896.51   484.1  909.77
#Mann= 7 ,-1 , 0
       0     .12       0  145.94    .016       0  189.98     .12       0
   195.7    .045       0   210.7     .12       0  325.86     .06       0
  355.85     .12       0
#XS Ineff= 2 , 0
                          312.97          891.38
Permanent Ineff=
       F       F
Bank Sta=195.7,210.7
XS Rating Curve= 0 ,0
Exp/Cntr=0.3,0.1