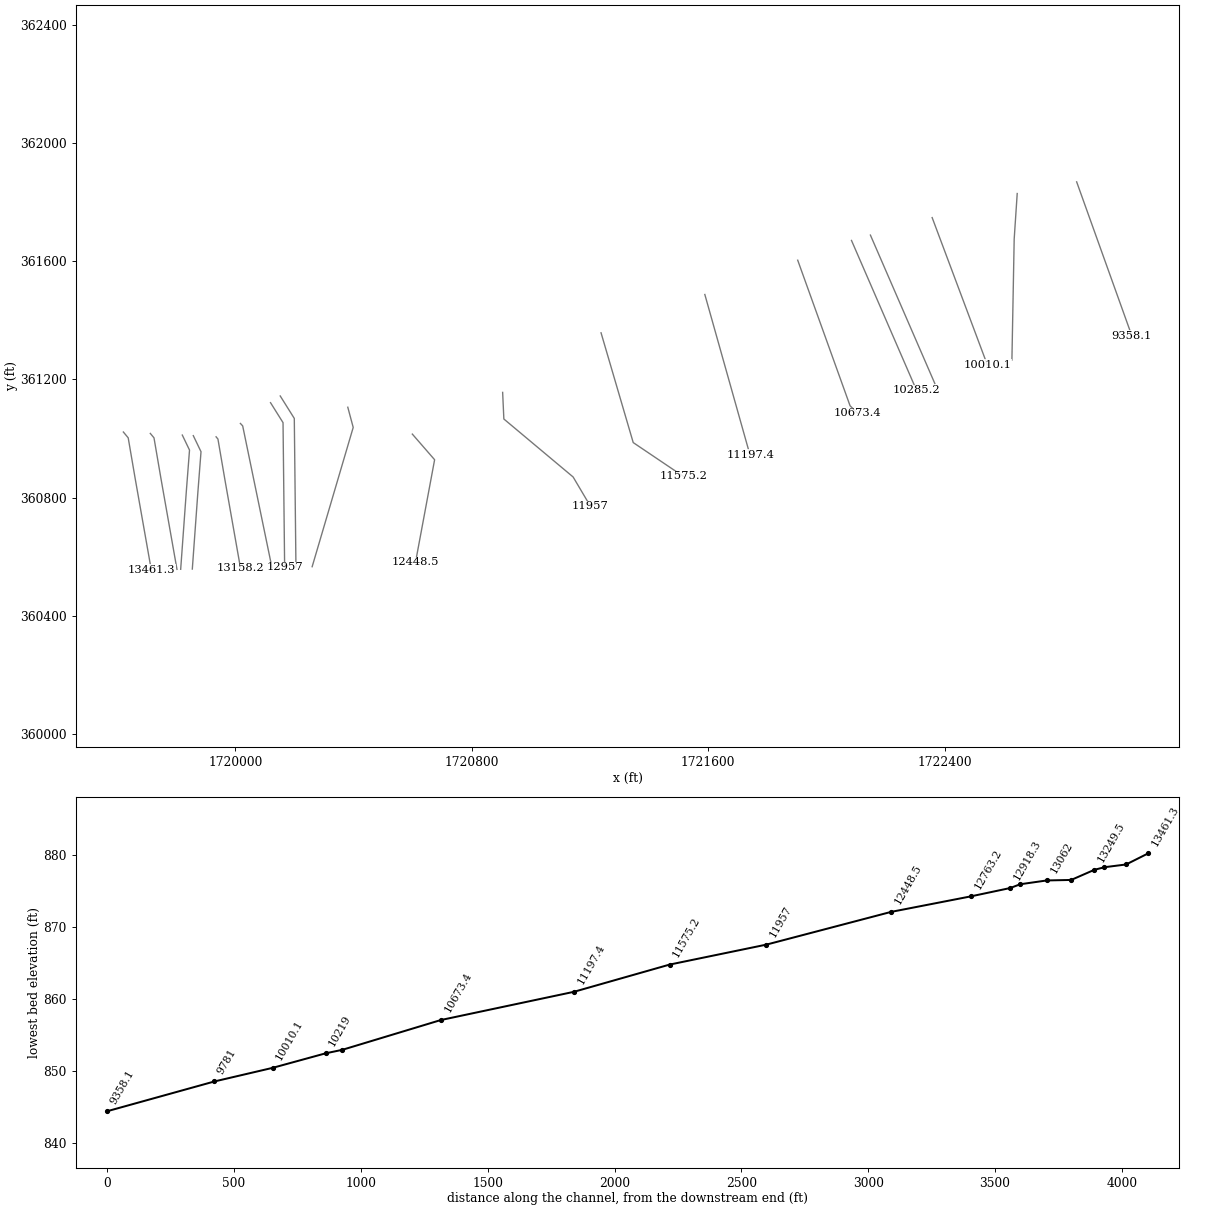
HEC-RAS study SIXMILECK.prj: SIXMILECK

--- SIXMILECK.g01 (geometry) --- (continued)

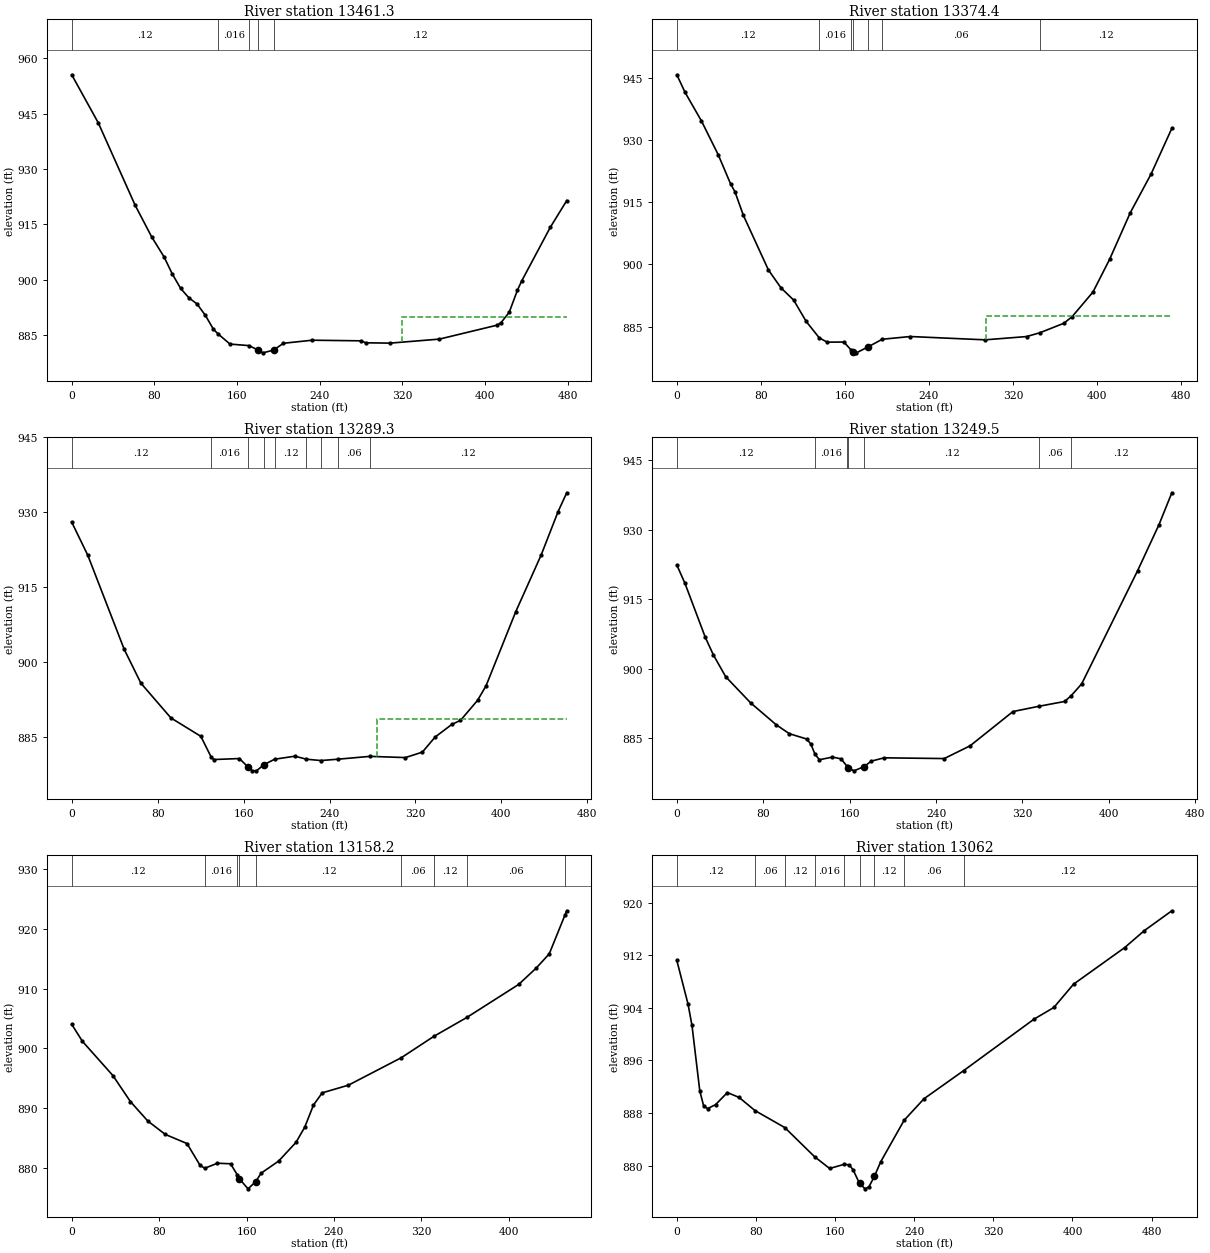
Type RM Length L Ch R = 1 ,13461.3 ,87.1,86.9,87.1
XS GIS Cut Line= 4
     1719620.922      361021.663      1719637.31      361001.995
     1719660.865      360864.431     1719715.393      360555.272
#Sta/Elev= 30
       0  955.49    25.6  942.53    61.5   920.1    77.4   911.6    89.4  906.17
    97.4  901.52   105.4  897.66   113.3  895.13   121.3  893.44   129.3  890.38
   137.2  886.58  141.74 885.305   153.2  882.58  171.71882.1638   180.3  880.96
     185  880.21   195.3  880.94   204.9   882.8   232.7  883.63   280.4  883.46
   284.4  882.93   308.2  882.84   355.9  883.93   411.5  887.69   415.5  888.36
   423.5  891.23   431.4  897.18   435.4   899.6   463.2  914.19   479.1  921.42
#Mann= 5 ,-1 , 0
       0     .12       0  141.74    .016       0  171.71     .12       0
   180.3    .045       0   195.3     .12       0
#XS Ineff= 2 , 0
                          319.27             890
Permanent Ineff=
       F       F
Bank Sta=180.3,195.3
XS Rating Curve= 0 ,0
Exp/Cntr=0.3,0.1

Type RM Length L Ch R = 1 ,13374.4 ,90.6,85.1,79.2
XS GIS Cut Line= 4
     1719712.106       361016.93      1719724.55      361001.995
     1719748.105      360864.431     1719802.332      360556.977
#Sta/Elev= 30
       0   945.8     7.8  941.56    23.4  934.66    39.4  926.49    51.3  919.38
    55.3  917.57    63.3  911.88    87.2  898.66    99.2  894.34   111.2  891.41
   123.1  886.26  135.58882.2832   143.1  881.25     159  881.28  165.55879.4458
   167.4  878.98   170.9  878.67   182.4  880.16  195.54  881.95   222.2  882.61
   293.4  881.81   332.9   882.6   345.5  883.51   368.5  885.82   376.4  887.44
   396.1  893.34   411.9  901.21   431.7  912.53   451.4  921.82   471.2  932.87
#Mann= 7 ,-1 , 0
       0     .12       0  135.58    .016       0  165.55     .12       0
   167.4    .045       0   182.4     .12       0  195.54     .06       0
   345.5     .12       0
#XS Ineff= 2 , 0
                          294.08          887.55
Permanent Ineff=
       F       F
Bank Sta=167.4,182.4
XS Rating Curve= 0 ,0
Exp/Cntr=0.3,0.1

Type RM Length L Ch R = 1 ,13289.3 ,39.8,39.8,39.7
XS GIS Cut Line= 4
     1719820.363       361011.31     1719844.772      360960.494
     1719833.996      360821.344     1719814.867      360557.222
#Sta/Elev= 30
       0  928.03      15  921.39    48.9  902.57    64.4  895.82    92.3  888.88
   120.2  885.19  129.57881.1468   132.1  880.55   156.1  880.75   163.7  879.14
     168  878.33     172  878.29   178.7  879.49  188.82880.6128   207.8  881.22
  218.43880.6199  231.98880.3476  248.05880.6225  277.66881.1846   310.6  880.94
   326.4  882.03   338.2  885.03     354   887.6   361.9  888.38   377.8  892.39
   385.7   895.3   413.3   910.1     437  921.46   452.8  930.16   460.8  933.91
#Mann= 9 ,-1 , 0
       0     .12       0  129.57    .016       0   163.7    .045       0
   178.7    .016       0  188.82     .12       0  218.43     .06       0
  231.98     .12       0  248.05     .06       0  277.66     .12       0
#XS Ineff= 2 , 0
                          284.63          888.57
Permanent Ineff=
       F       F
Bank Sta=163.7,178.7
XS Rating Curve= 0 ,0
Exp/Cntr=0.3,0.1

Type RM Length L Ch R = 1 ,13249.5 ,85.7,91.4,97.1
XS GIS Cut Line= 4
     1719857.541       361009.38     1719883.669      360954.988
     1719872.892      360815.838     1719854.218      360557.994
#Sta/Elev= 30
       0  922.35     7.5  918.41    26.4  906.72    33.9  902.92    45.3  898.23
    68.3  892.61    92.2  887.84   104.2  885.95   120.2   884.8   124.1  883.71
  128.02881.4658   132.1  880.33   144.1   880.9   152.1  880.52  157.64878.8946
   158.5  878.64     164  877.93   173.5  878.85     180  880.02   191.9  880.74
   247.6  880.58   271.5  883.32   311.3  890.73  335.33891.8657     359   892.9
  364.94894.0878   374.9   896.7   426.6  921.08   446.5  931.07   458.4  937.95
#Mann= 7 ,-1 , 0
       0     .12       0  128.02    .016       0  157.64     .12       0
   158.5    .045       0   173.5     .12       0  335.33     .06       0
  364.94     .12       0
Bank Sta=158.5,173.5
XS Rating Curve= 0 ,0
Exp/Cntr=0.3,0.1

Type RM Length L Ch R = 1 ,13158.2 ,95.5,96.2,96.9
XS GIS Cut Line= 4
     1719934.666      361005.377     1719940.956      360997.829
     1719964.511      360860.265      1720017.26      360561.191
#Sta/Elev= 30
       0  904.01     9.8  901.17    37.7  895.45    53.7  891.11    69.6  887.86
    85.6  885.62   105.5  884.09   117.5  880.44  121.75879.9587   133.4   880.8
   145.4  880.71  151.72878.8093   153.3  878.23   161.4  876.52   168.3  877.71
   173.4  879.14   189.4  881.16   205.3  884.29   213.3  886.83   221.3  890.53
   229.3  892.56   253.3  893.85  301.67898.4323  331.66902.0237  361.65905.1605
   409.1  910.68   425.1   913.4   437.1  915.79  451.63922.3395   453.1  922.99
#Mann= 9 ,-1 , 0
       0     .12       0  121.75    .016       0  151.72     .12       0
   153.3    .045       0   168.3     .12       0  301.67     .06       0
  331.66     .12       0  361.65     .06       0  451.63     .12       0
Bank Sta=153.3,168.3
XS Rating Curve= 0 ,0
Exp/Cntr=0.3,0.1

Type RM Length L Ch R = 1 ,13062   ,109.2,105,100.5
XS GIS Cut Line= 3
     1720016.932      361050.647     1720024.639      361042.411
     1720123.635      360563.277
#Sta/Elev= 30
       0  911.23    11.3  904.59    15.3  901.34    23.2  891.36    27.2  889.02
    31.2  888.68    39.1  889.27    51.1  891.11      63  890.37   78.98 888.371
  109.14885.7833   139.3881.3367   154.5  879.55  169.46880.1953   174.4  880.09
   178.3  879.32   184.7  877.27   190.3  876.45   194.2  876.75   199.7  878.34
   206.2  880.59  229.77886.8846   249.9  890.17  290.09894.4656   361.3  902.31
   381.2  904.07   401.1  907.62   452.8  913.19   472.7  915.78   500.5   918.8
#Mann= 9 ,-1 , 0
       0     .12       0   78.98     .06       0  109.14     .12       0
   139.3    .016       0  169.46     .12       0   184.7    .045       0
   199.7     .12       0  229.77     .06       0  290.09     .12       0
Bank Sta=184.7,199.7
XS Rating Curve= 0 ,0
Exp/Cntr=0.3,0.1

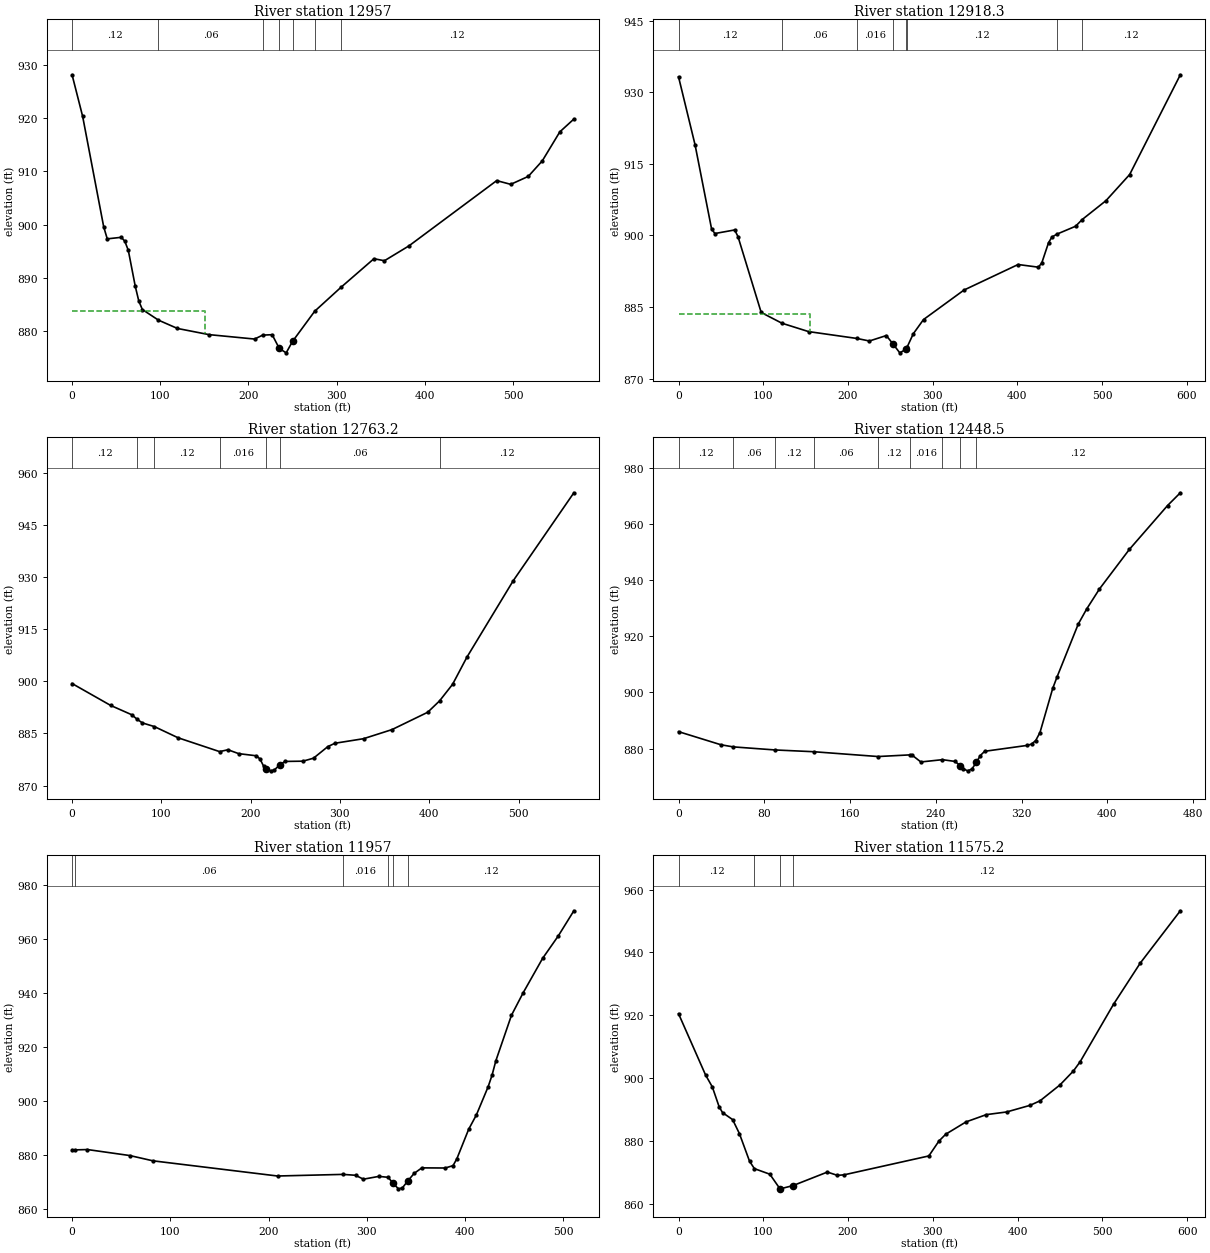
Type RM Length L Ch R = 1 ,12957   ,38.7,38.7,38.8
XS GIS Cut Line= 3
     1720118.859      361120.941      1720161.18      361053.393
     1720166.633       360564.12
#Sta/Elev= 30
       0  928.15      12  920.33    35.9  899.56    39.9  897.33    55.8  897.62
    59.8   896.9    63.8  895.15    71.7  888.39    75.7  885.63    79.7  884.06
   97.93882.0629   119.5   880.5   155.3  879.34     207  878.51  216.07 879.244
   226.9  879.33     235  876.74   242.8  875.92     250  878.07  275.15 883.738
  304.69 888.194   342.3   893.6   354.2  893.22     382  896.01   481.5  908.27
   497.4  907.57   517.3  909.06   533.2  911.98   553.1  917.43     569  919.83
#Mann= 7 ,-1 , 0
       0     .12       0   97.93     .06       0  216.07    .016       0
     235    .045       0     250     .12       0  275.15     .06       0
  304.69     .12       0
#XS Ineff= 2 , 0
          150.38   883.7
Permanent Ineff=
       F       F
Bank Sta=235,250
XS Rating Curve= 0 ,0
Exp/Cntr=0.3,0.1

Type RM Length L Ch R = 1 ,12918.3 ,161.8,155.1,148.4
XS GIS Cut Line= 3
     1720151.711      361143.598     1720199.304      361067.635
     1720204.908       360564.87
#Sta/Elev= 30
       0  933.21    19.5  918.98      39  901.36    42.9  900.39    66.3  901.14
    70.2  899.74    97.6  883.85   122.1881.6025   153.5  879.85  210.71878.4097
   225.3  877.88   245.3  879.02   253.3  877.23   261.2   875.4   268.3  876.13
  269.78876.5709   277.2  879.41   289.2  882.37     337  888.55   400.9   893.9
   424.8  893.34   428.8  894.21   436.8  898.46   440.8  899.66  447.01900.2858
   468.7  901.91  476.54903.3184   504.6  907.27   532.6  912.75   592.4  933.64
#Mann= 8 ,-1 , 0
       0     .12       0   122.1     .06       0  210.71    .016       0
   253.3    .045       0   268.3    .016       0  269.78     .12       0
  447.01     .06       0  476.54     .12       0
#XS Ineff= 2 , 0
          154.91  883.48
Permanent Ineff=
       F       F
Bank Sta=253.3,268.3
XS Rating Curve= 0 ,0
Exp/Cntr=0.3,0.1

Type RM Length L Ch R = 1 ,12763.2 ,312.2,314.6,316.9
XS GIS Cut Line= 3
     1720380.312       361105.52     1720398.629      361037.192
     1720259.731      360565.945
#Sta/Elev= 30
       0  899.37    43.2  893.07    66.8  890.39   72.85889.0885    78.7  888.04
   92.17886.9783   118.7  883.76  165.22879.7745   174.6  880.31   186.6  879.19
   206.5  878.57   210.5  877.64   214.5   875.6   217.7  874.78   222.5  874.24
   226.5  874.48   232.7  875.99   238.5  876.95   258.5  877.02   270.4  877.88
   286.4  881.21   294.4  882.18   326.4  883.49   358.3  886.11   398.3   891.1
  411.55894.3646   426.2  899.16   442.2  906.95   494.1  928.97     562  954.28
#Mann= 7 ,-1 , 0
       0     .12       0   72.85    .016       0   92.17     .12       0
  165.22    .016       0   217.7    .045       0   232.7     .06       0
  411.55     .12       0
Bank Sta=217.7,232.7
XS Rating Curve= 0 ,0
Exp/Cntr=0.3,0.1

Type RM Length L Ch R = 1 ,12448.5 ,467,491.5,515.7
XS GIS Cut Line= 3
     1720598.677      361014.601     1720674.085      360927.882
     1720609.426      360580.773
#Sta/Elev= 30
       0  886.04    39.6  881.36   51.04880.6095   90.18879.5153  125.97878.8907
  186.06877.1755   216.1  877.77   218.1  877.59     226  875.24  246.14876.0583
   257.7  875.44   262.8  873.94   265.7  872.81   269.6  872.08   273.6  872.71
   277.8  875.11   281.5  877.54   285.5  879.04   325.2  881.14   329.2  881.61
   333.1  882.86   337.1  885.72     349  901.46     353  905.49   372.8  924.35
   380.7  929.75   392.6  936.86   420.4  950.91   456.1  966.57     468  971.11
#Mann= 9 ,-1 , 0
       0     .12       0   51.04     .06       0   90.18     .12       0
  125.97     .06       0  186.06     .12       0   216.1    .016       0
  246.14     .12       0   262.8    .045       0   277.8     .12       0
Bank Sta=262.8,277.8
XS Rating Curve= 0 ,0
Exp/Cntr=0.3,0.1

Type RM Length L Ch R = 1 ,11957   ,395,381.8,368.2
XS GIS Cut Line= 4
     1720904.253      361155.763     1720908.344      361065.688
     1721142.719      360869.508     1721201.316      360770.498
#Sta/Elev= 30
       0  881.96    2.48881.9409    15.7  882.07    58.8  879.85    82.3   877.9
   209.2  872.28   275.8 872.877   288.6  872.55   296.6   871.1   312.4  872.14
  321.82871.7904     327  869.52   332.3  867.53   336.3  867.88     342  870.53
   348.2  873.22   356.1  875.29   379.9  875.24   387.9  876.12   391.8  878.68
   403.8  889.57   411.7  894.92   423.6  905.29   427.6  909.59   431.5  914.96
   447.4  931.79   459.3   940.1   479.1  952.84     495  961.11   510.9  970.44
#Mann= 6 ,-1 , 0
       0     .12       0    2.48     .06       0   275.8    .016       0
  321.82     .12       0     327    .045       0     342     .12       0
Bank Sta=327,342
XS Rating Curve= 0 ,0
Exp/Cntr=0.3,0.1

Type RM Length L Ch R = 1 ,11575.2 ,377.8,377.8,378
XS GIS Cut Line= 3
     1721237.208      361357.328     1721346.077      360985.898
     1721516.037      360871.379
#Sta/Elev= 30
       0   920.5    31.9  900.99    39.9  897.17    47.9  890.87    51.9  889.02
    63.8  886.79    71.8  882.35    83.8  873.52   89.53871.1759   107.7  869.41
   119.7  864.75     120  864.75     135  865.78   175.6  870.09   187.5  869.03
   195.5  869.22   295.3  875.22   307.2  879.95   315.2  882.13   339.2  886.06
   363.1  888.37   387.1  889.22   414.6  891.32   426.5  892.77   450.1  897.85
   465.9  902.28   473.8   905.2   513.2   923.5   544.7   936.6     592  953.26
#Mann= 4 ,-1 , 0
       0     .12       0   89.53    .016       0     120    .045       0
     135     .12       0
Bank Sta=120,135
XS Rating Curve= 0 ,0
Exp/Cntr=0.3,0.1

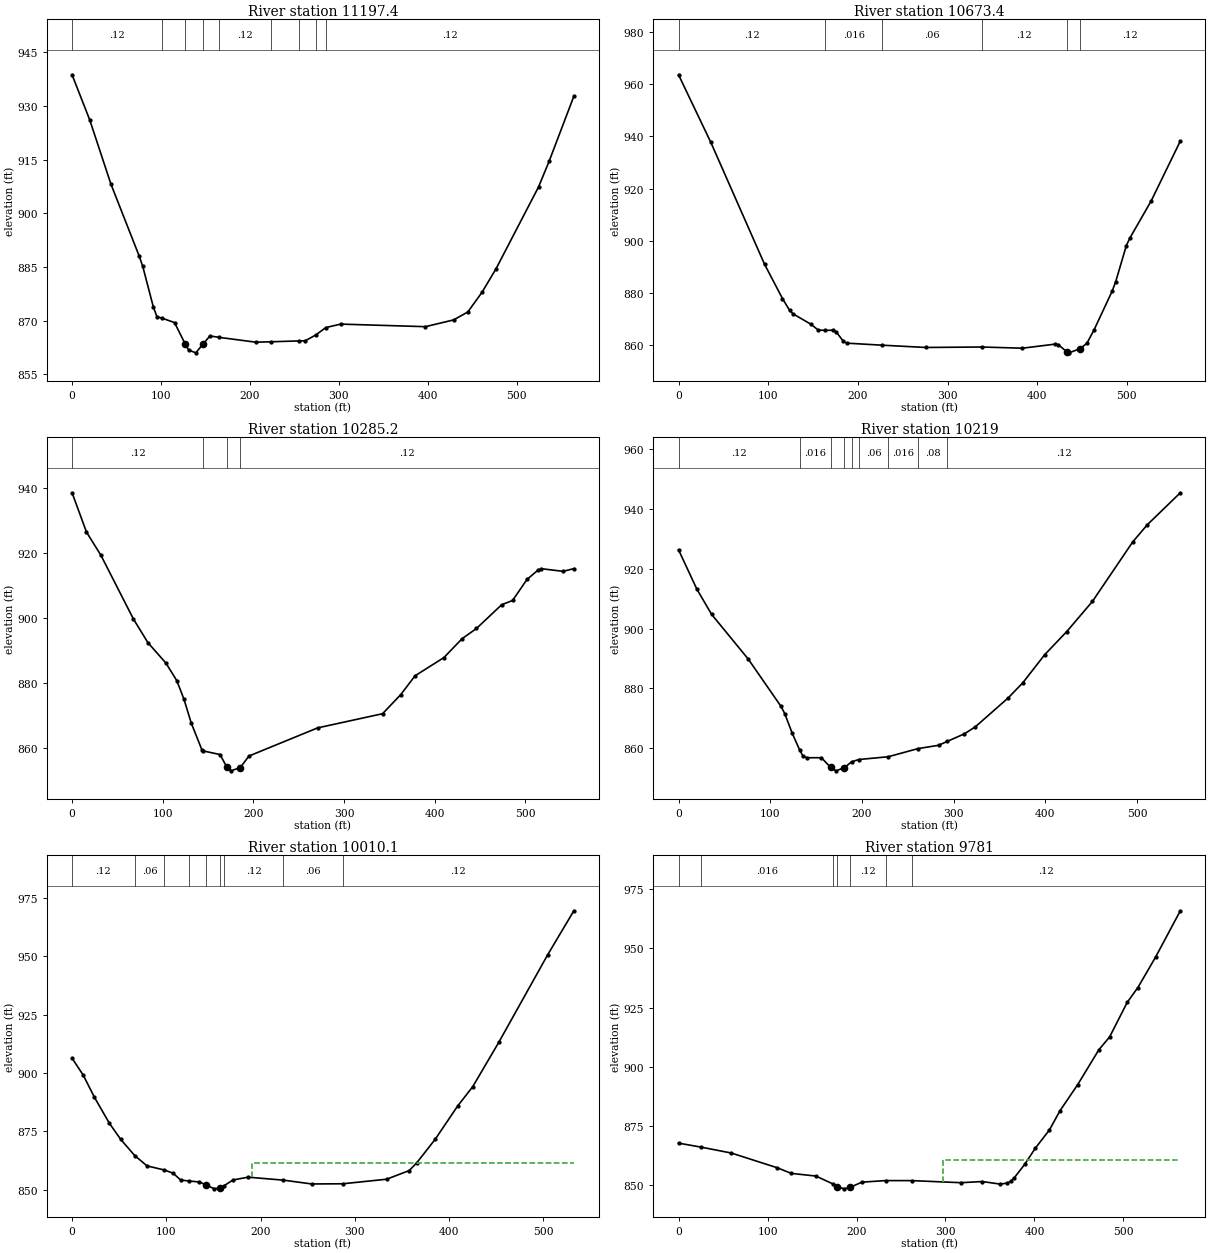
Type RM Length L Ch R = 1 ,11197.4 ,521.5,524,526.2
XS GIS Cut Line= 2
     1721588.368      361486.987     1721741.226      360943.871
#Sta/Elev= 30
       0  938.76    19.9  926.11    43.7  908.16    75.5  888.02    79.5  885.12
    91.4  873.78    95.4  871.09  101.23870.6455   115.2  869.43   127.2  863.44
   131.1  861.74   139.1  860.96     147  863.34     155  865.69  164.97865.3041
   206.6  863.94  223.96864.0573  254.64864.2949   262.2  864.33  273.98865.9598
  285.33 868.031     302     869   397.3  868.28   429.1  870.18     445   872.4
   460.9  877.89   476.8  884.53   524.5  907.38   536.4  914.57   564.2  932.76
#Mann= 9 ,-1 , 0
       0     .12       0  101.23    .016       0   127.2    .045       0
     147    .016       0  164.97     .12       0  223.96     .06       0
  254.64     .12       0  273.98     .06       0  285.33     .12       0
Bank Sta=127.2,147
XS Rating Curve= 0 ,0
Exp/Cntr=0.3,0.1

Type RM Length L Ch R = 1 ,10673.4 ,388,388.2,393.6
XS GIS Cut Line= 3
     1721902.603      361603.012     1722079.738      361110.523
     1722105.385      361084.876
#Sta/Elev= 30
       0  963.65      36  937.74    95.9  891.02   115.9  877.87   123.8  873.34
   127.8  871.97   147.8  867.97   155.8  865.77  163.55865.6625   171.8  865.72
   175.8   865.1   183.8  861.45   187.8  860.75  226.87859.9766   275.7   859.1
  338.06859.2762   383.5  858.82   419.5  860.36   423.5  860.19   433.2  857.37
   435.5  857.04   448.2  858.69   455.5  860.75   463.4  865.85   483.4  880.56
   487.4  884.18   499.4  898.16   503.4   901.1     527  915.22   559.6  938.24
#Mann= 6 ,-1 , 0
       0     .12       0  163.55    .016       0  226.87     .06       0
  338.06     .12       0   433.2    .045       0   448.2     .12       0
Bank Sta=433.2,448.2
XS Rating Curve= 0 ,0
Exp/Cntr=0.3,0.1

Type RM Length L Ch R = 1 ,10285.2 ,66.1,66.1,66.1
XS GIS Cut Line= 2
     1722084.611      361669.847     1722304.981       361162.16
#Sta/Elev= 30
       0  938.42    15.9  926.34    31.8   919.2    67.7  899.58    83.6  892.34
   103.5  886.04   115.5  880.64   123.4  874.94   131.4  867.63   143.3  859.28
  144.61859.0278   163.2  857.91   170.5  854.14   175.2   852.9   185.5  853.91
   195.1  857.46   270.8  866.11   342.4  870.47   362.3  876.28   378.3  882.14
   410.1  887.74     430  893.51     446  896.68   473.8  903.99   485.8  905.29
   501.7  911.76   513.6  914.58   517.6  915.07   541.5  914.26   553.4  915.09
#Mann= 4 ,-1 , 0
       0     .12       0  144.61    .016       0   170.5    .045       0
   185.5     .12       0
Bank Sta=170.5,185.5
XS Rating Curve= 0 ,0
Exp/Cntr=0.3,0.1

Type RM Length L Ch R = 1 ,10219   ,210,208.9,207.7
XS GIS Cut Line= 2
       1722148.6      361687.963     1722366.495      361185.979
#Sta/Elev= 30
       0  926.38      20   913.2      36   904.8    75.9  889.86   111.8  873.96
   115.8  871.58   123.8  865.12  132.16859.3293   135.8   857.3   139.8   856.8
   155.8   856.8   165.9  853.56   171.8  852.41   180.9   853.5   188.8855.4362
  196.56856.1965  228.75857.1282  260.95859.8406   283.6  860.96  293.15862.2809
   311.6  864.78   323.6  867.12   359.5  876.82   375.5   881.9   399.4  891.32
   423.4  899.03   451.4  909.13   495.3  929.02   511.3   934.8   547.2  945.46
#Mann= 9 ,-1 , 0
       0     .12       0  132.16    .016       0   165.9    .045       0
   180.9    .016       0   188.8     .12       0  196.56     .06       0
  228.75    .016       0  260.95     .08       0  293.15     .12       0
Bank Sta=165.9,180.9
XS Rating Curve= 0 ,0
Exp/Cntr=0.3,0.1

Type RM Length L Ch R = 1 ,10010.1 ,237.5,229.2,220.6
XS GIS Cut Line= 2
     1722357.545      361747.116     1722544.368       361248.45
#Sta/Elev= 30
       0  906.32    11.9  899.04    23.8  889.54    39.7   878.4    51.7  871.53
   66.48864.6424    79.5  860.22   98.02858.4507   107.3  857.06   115.2  854.18
  123.84 853.742   135.1  853.34   142.2  852.07     151  850.39   157.2   850.9
   161.1  851.68   170.9   854.2   186.8  855.38  224.18854.1178   254.3  852.48
  287.26 852.558   333.8  854.51   357.7   858.2   365.6  861.45   385.5  871.69
   409.3  885.93   425.2  894.15     453  913.25   504.7  950.61   532.5  969.46
#Mann= 9 ,-1 , 0
       0     .12       0   66.48     .06       0   98.02     .12       0
  123.84    .016       0   142.2    .045       0   157.2    .016       0
   161.1     .12       0  224.18     .06       0  287.26     .12       0
#XS Ineff= 2 , 0
                          190.43          861.43
Permanent Ineff=
       F       F
Bank Sta=142.2,157.2
XS Rating Curve= 0 ,0
Exp/Cntr=0.3,0.1

Type RM Length L Ch R = 1 ,9781    ,408.9,422.8,432.9
XS GIS Cut Line= 3
      1722645.33       361828.59     1722635.094      361674.511
     1722627.385      361265.119
#Sta/Elev= 30
       0  867.79   25.65866.0692    59.4   863.6   110.9  857.39   126.7  855.02
   154.4  853.89  173.61850.5515     178  849.38   186.2   848.5     193  849.16
   206.1  851.32  232.69851.9804  262.23851.9667   317.4  851.09   341.3  851.58
   361.1  850.52   369.1  850.88   373.1   851.6     377  853.02     389  858.82
   400.9  865.62   416.8  873.35   428.7  881.46   448.6  892.49   472.4  907.21
   484.4  912.56   504.2  927.16   516.2  933.42   536.1  946.28   563.9  965.81
#Mann= 7 ,-1 , 0
       0     .12       0   25.65    .016       0  173.61     .12       0
     178    .045       0     193     .12       0  232.69     .06       0
  262.23     .12       0
#XS Ineff= 2 , 0
                          297.73          860.54
Permanent Ineff=
       F       F
Bank Sta=178,193
XS Rating Curve= 0 ,0
Exp/Cntr=0.3,0.1

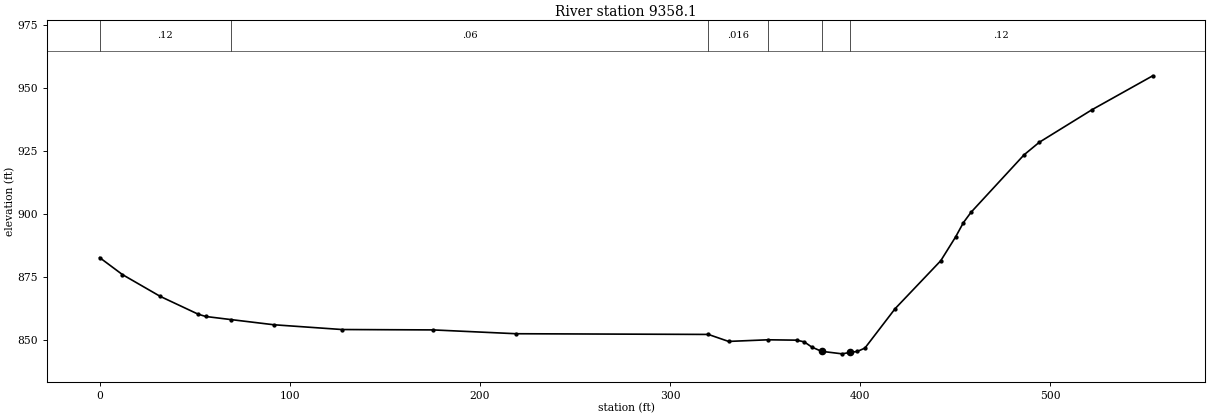
Type RM Length L Ch R = 1 ,9358.1  ,373.4,375.3,375.9
XS GIS Cut Line= 2
     1722846.449      361868.086     1723033.357      361346.636
#Sta/Elev= 30
       0  882.57      12  875.82    31.9  867.16    51.8  860.11    55.8  859.19
   69.15857.9512    91.7   855.9   127.5  854.01   175.4  853.86   219.2  852.34
  320.16852.0646   330.8  849.29  351.54 849.939   366.6  849.79   370.6  849.11
   374.6  847.03   379.7  845.36   390.5  844.36   394.7  844.92   398.5  845.31
   402.5  846.64   418.4   862.3   442.4  881.33   450.3   890.9   454.3  896.44
   458.3  900.54   486.2  923.36   494.2  928.34     522   941.3   553.9  954.75
#Mann= 6 ,-1 , 0
       0     .12       0   69.15     .06       0  320.16    .016       0
  351.54     .12       0   379.7    .045       0   394.7     .12       0
Bank Sta=379.7,394.7
XS Rating Curve= 0 ,0
Exp/Cntr=0.3,0.1