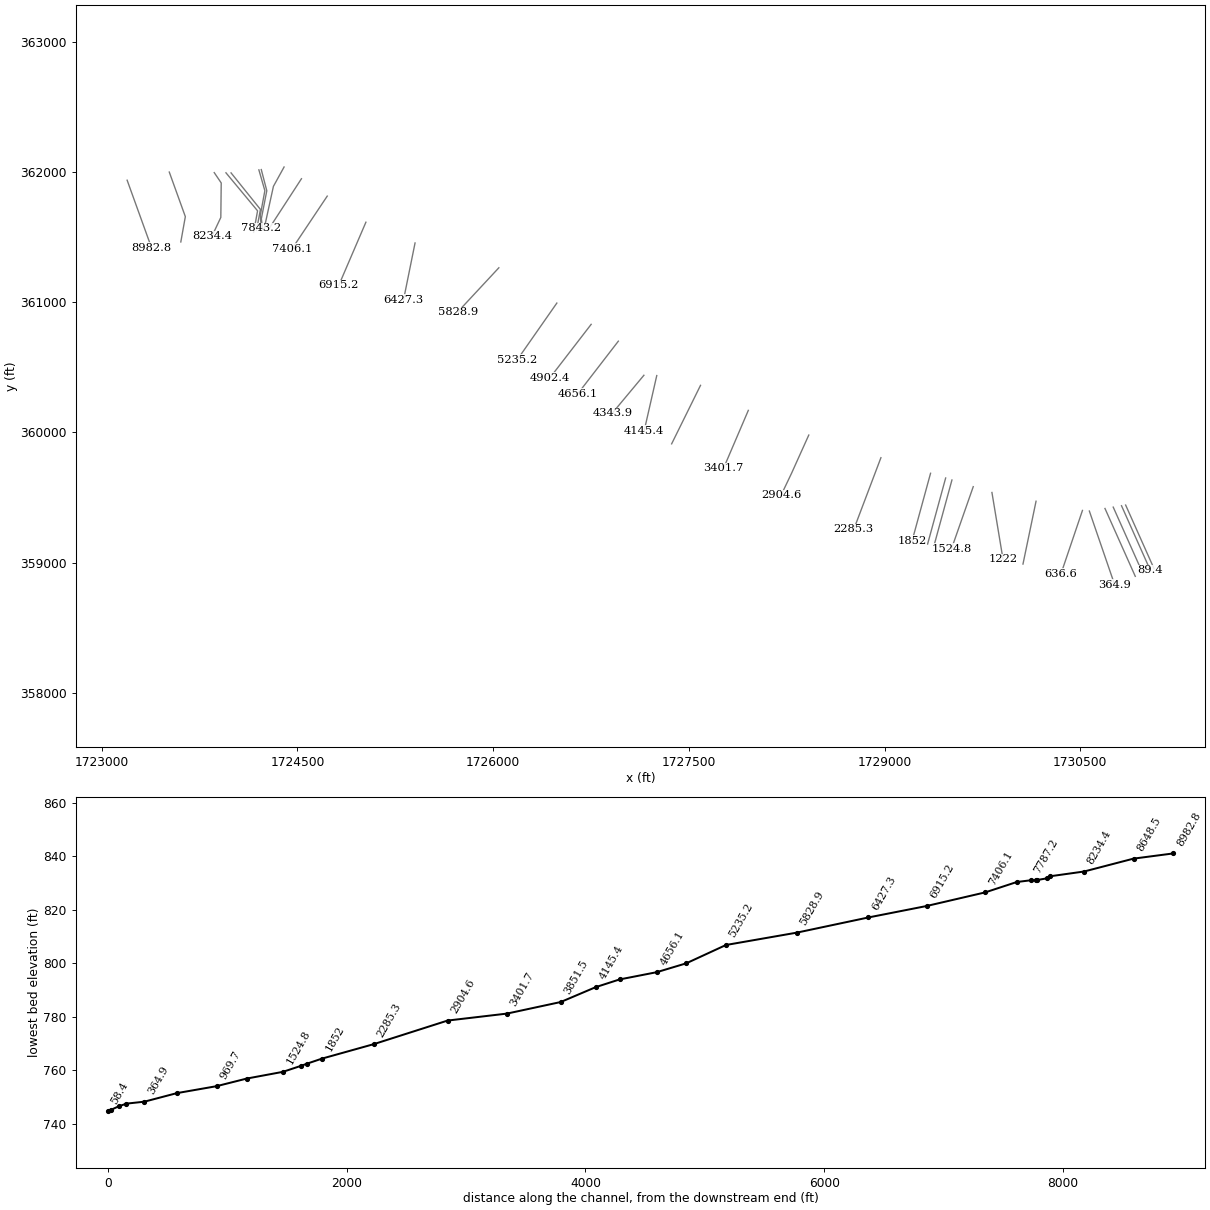
HEC-RAS study SIXMILECK.prj: SIXMILECK

--- SIXMILECK.g01 (geometry) --- (continued)

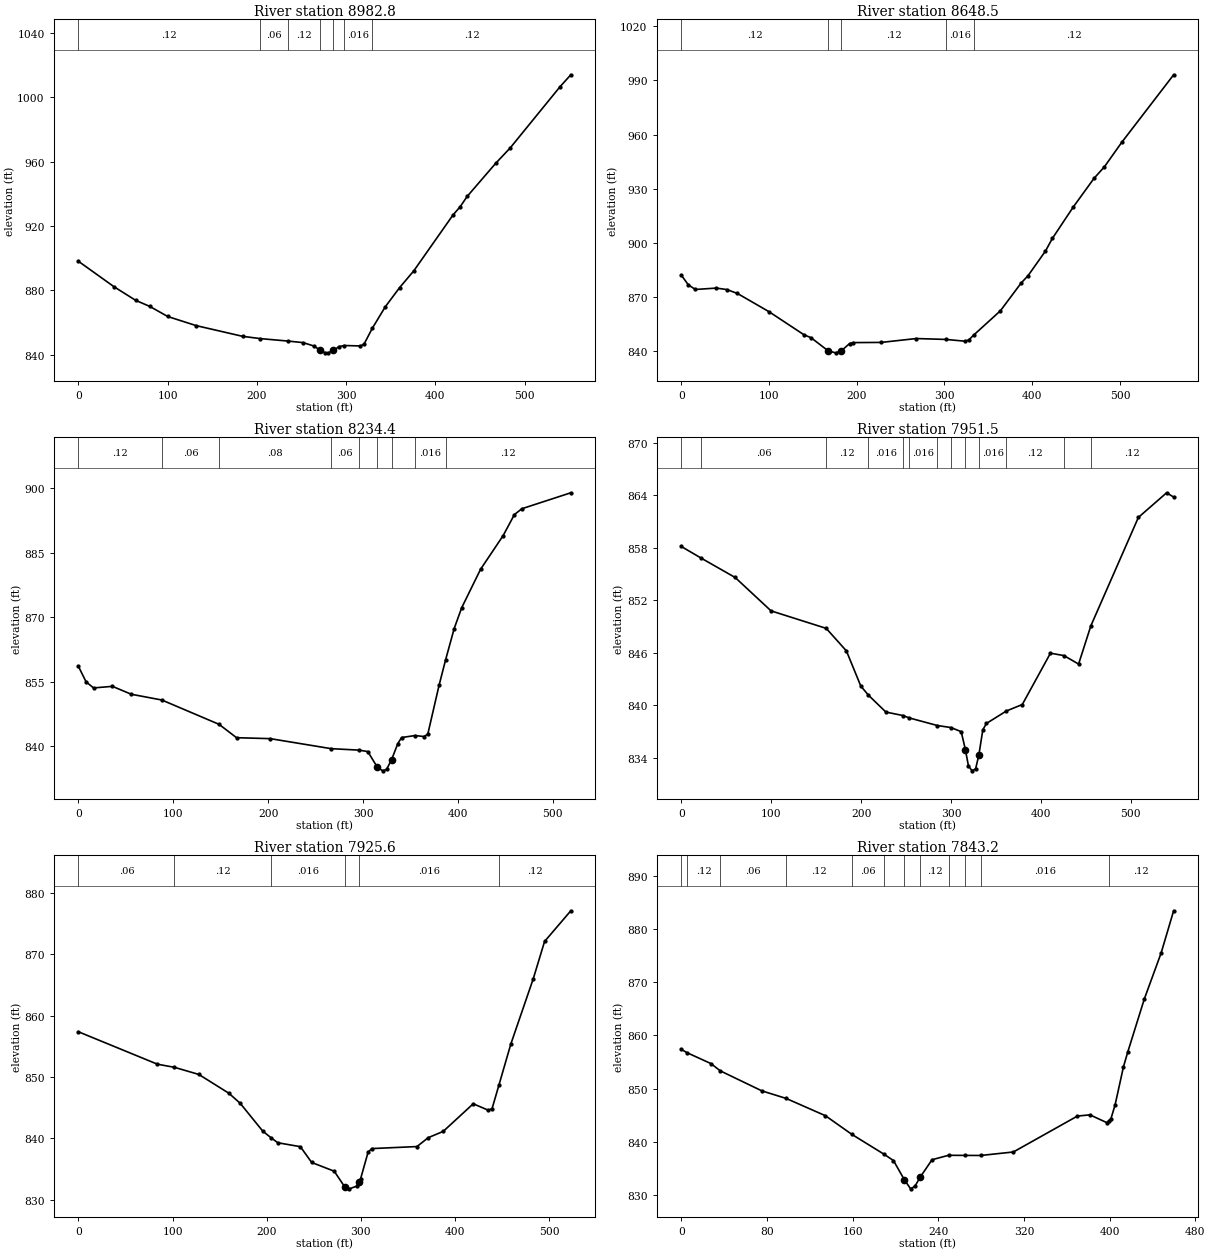
Type RM Length L Ch R = 1 ,8982.8  ,334.4,334.3,334.4
XS GIS Cut Line= 2
      1723194.54      361935.626      1723381.69       361416.58
#Sta/Elev= 30
       0  897.97      40   882.1      64  873.73      80   869.9     100  863.66
   131.9  857.99   183.9  851.33  203.81 849.905   235.2848.3645   251.9   847.4
   263.9  845.29   270.8  842.74   275.9  841.22   279.9  841.06   285.8  842.53
   291.9  844.91     298845.6088   315.9  845.35   319.9  846.32  329.39856.3981
   343.8  869.64   359.8  881.54   375.8  892.04   419.8   926.8   427.8  931.92
   435.8  938.43   467.8  959.03   483.8  968.43   539.8 1006.58   551.8 1013.95
#Mann= 7 ,-1 , 0
       0     .12       0  203.81     .06       0   235.2     .12       0
   270.8    .045       0   285.8     .12       0     298    .016       0
  329.39     .12       0
Bank Sta=270.8,285.8
XS Rating Curve= 0 ,0
Exp/Cntr=0.3,0.1

Type RM Length L Ch R = 1 ,8648.5  ,421.9,414.1,406.2
XS GIS Cut Line= 3
     1723517.494      361998.289     1723640.664      361656.058
      1723605.98      361461.616
#Sta/Elev= 30
       0  882.14       8  876.78      16  874.21      40  874.98      52  874.15
      64  871.99    99.9  861.92   139.9   849.1   147.9   847.5   167.3  840.24
   175.9  839.11   182.3  840.18   191.8  844.24   195.8  844.78   227.8  844.88
   267.8  847.03  301.77846.5298   323.8  845.54   327.8   846.3  333.16848.8968
   363.7  862.39   387.4  877.79   395.3  881.88   415.1   895.5     423  902.52
   446.7  919.83   470.4  935.74   482.2  942.11     502  955.68   561.2  993.13
#Mann= 5 ,-1 , 0
       0     .12       0   167.3    .045       0   182.3     .12       0
  301.77    .016       0  333.16     .12       0
Bank Sta=167.3,182.3
XS Rating Curve= 0 ,0
Exp/Cntr=0.3,0.1

Type RM Length L Ch R = 1 ,8234.4  ,266.7,282.9,295
XS GIS Cut Line= 4
     1723862.177      361993.925     1723915.675      361914.777
      1723912.61      361649.884     1723844.892      361506.239
#Sta/Elev= 30
       0  858.58       8  855.02    15.9  853.59    35.8  853.96    55.7  852.12
   87.92  850.78   148.3 845.117   166.7  842.01   202.3  841.79  266.45  839.46
  295.98839.1195   305.1  838.78   315.2  835.14   320.9   834.3   324.9  834.64
   330.2  836.91   336.7  840.61   340.7  842.05  355.06842.5116   364.4  842.28
   368.4  842.86   380.3  854.24  387.14860.1204   396.2  867.41   404.1  872.24
     424  881.19   447.8  889.02   459.7  893.93   467.6  895.29   519.2     899
#Mann= 9 ,-1 , 0
       0     .12       0   87.92     .06       0   148.3     .08       0
  266.45     .06       0  295.98     .12       0   315.2    .045       0
   330.2     .12       0  355.06    .016       0  387.14     .12       0
Bank Sta=315.2,330.2
XS Rating Curve= 0 ,0
Exp/Cntr=0.3,0.1

Type RM Length L Ch R = 1 ,7951.5  ,26.2,25.9,29.2
XS GIS Cut Line= 3
     1723952.023      361992.484      1724194.26      361700.775
      1724164.34      361535.146
#Sta/Elev= 30
       0  858.14   22.46856.7893    59.9   854.6    99.8  850.79  161.15848.7927
   183.6  846.22   199.6  842.21  207.99 841.177   227.5  839.24  246.38838.8452
  253.61838.5671  284.77837.7023  299.84837.4714   311.3     837   315.9  834.95
   319.3   833.1   323.3  832.53   327.3  832.76   330.9  834.34   335.3  837.21
   339.3  837.94  361.55839.3629   379.2   840.1   410.5  845.96  425.43845.6861
   441.8  844.72  455.44849.0844   508.3  861.46   539.7  864.27   547.5  863.78
#Mann= 13 ,-1 , 0
       0     .12       0   22.46     .06       0  161.15     .12       0
  207.99    .016       0  246.38     .06       0  253.61    .016       0
  284.77     .12       0  299.84    .016       0   315.9    .045       0
   330.9    .016       0  361.55     .12       0  425.43    .016       0
  455.44     .12       0
Bank Sta=315.9,330.9
XS Rating Curve= 0 ,0
Exp/Cntr=0.3,0.1

Type RM Length L Ch R = 1 ,7925.6  ,102,82.3,62.6
XS GIS Cut Line= 3
     1723991.152      361991.856      1724216.32      361711.309
     1724185.938      361550.719
#Sta/Elev= 30
       0  857.36    83.9  852.08  101.97 851.572   127.9  850.41   159.9  847.34
   171.9   845.7   195.8  841.18  204.37840.1288   211.8  839.28   235.8  838.64
   247.8  836.07   271.8  834.64   283.2  832.03   287.8  831.77   295.8  832.22
   298.2  832.93   299.8   833.4   307.8  837.76   311.8  838.33   359.7  838.66
   371.7  840.11   387.6  841.13   419.5  845.63   435.5  844.58   439.5  844.83
  446.84848.6984   459.4  855.34   483.3  866.01   495.3  872.08   523.2  877.08
#Mann= 6 ,-1 , 0
       0     .06       0  101.97     .12       0  204.37    .016       0
   283.2    .045       0   298.2    .016       0  446.84     .12       0
Bank Sta=283.2,298.2
XS Rating Curve= 0 ,0
Exp/Cntr=0.3,0.1

Type RM Length L Ch R = 1 ,7843.2  ,14.5,14.5,14.6
XS GIS Cut Line= 4
     1724204.254      362015.176     1724250.174      361855.406
     1724214.584      361662.698     1724224.132      361565.476
#Sta/Elev= 30
       0  857.38    5.72856.7263    27.7  854.71   36.45 853.338    75.2  849.58
   97.91848.1517   134.6   844.9  159.37841.3782  189.56837.6224   198.2  836.45
   208.4  832.83   214.2  831.13   218.2  831.61   223.4   833.4   234.2  836.61
  249.63837.4443   265.3837.4245  279.67 837.411   310.2  838.07     370  844.83
   381.7  845.06   397.4   843.6  399.36843.9568   401.3  844.31   405.2  846.93
     413  854.09   416.9   856.8   432.5  866.87   448.2  875.53   459.9  883.48
#Mann= 12 ,-1 , 0
       0     .06       0    5.72     .12       0   36.45     .06       0
   97.91     .12       0  159.37     .06       0  189.56     .12       0
   208.4    .045       0   223.4     .12       0  249.63    .016       0
   265.3     .06       0  279.67    .016       0  399.36     .12       0
Bank Sta=208.4,223.4
XS Rating Curve= 0 ,0
Exp/Cntr=0.3,0.1

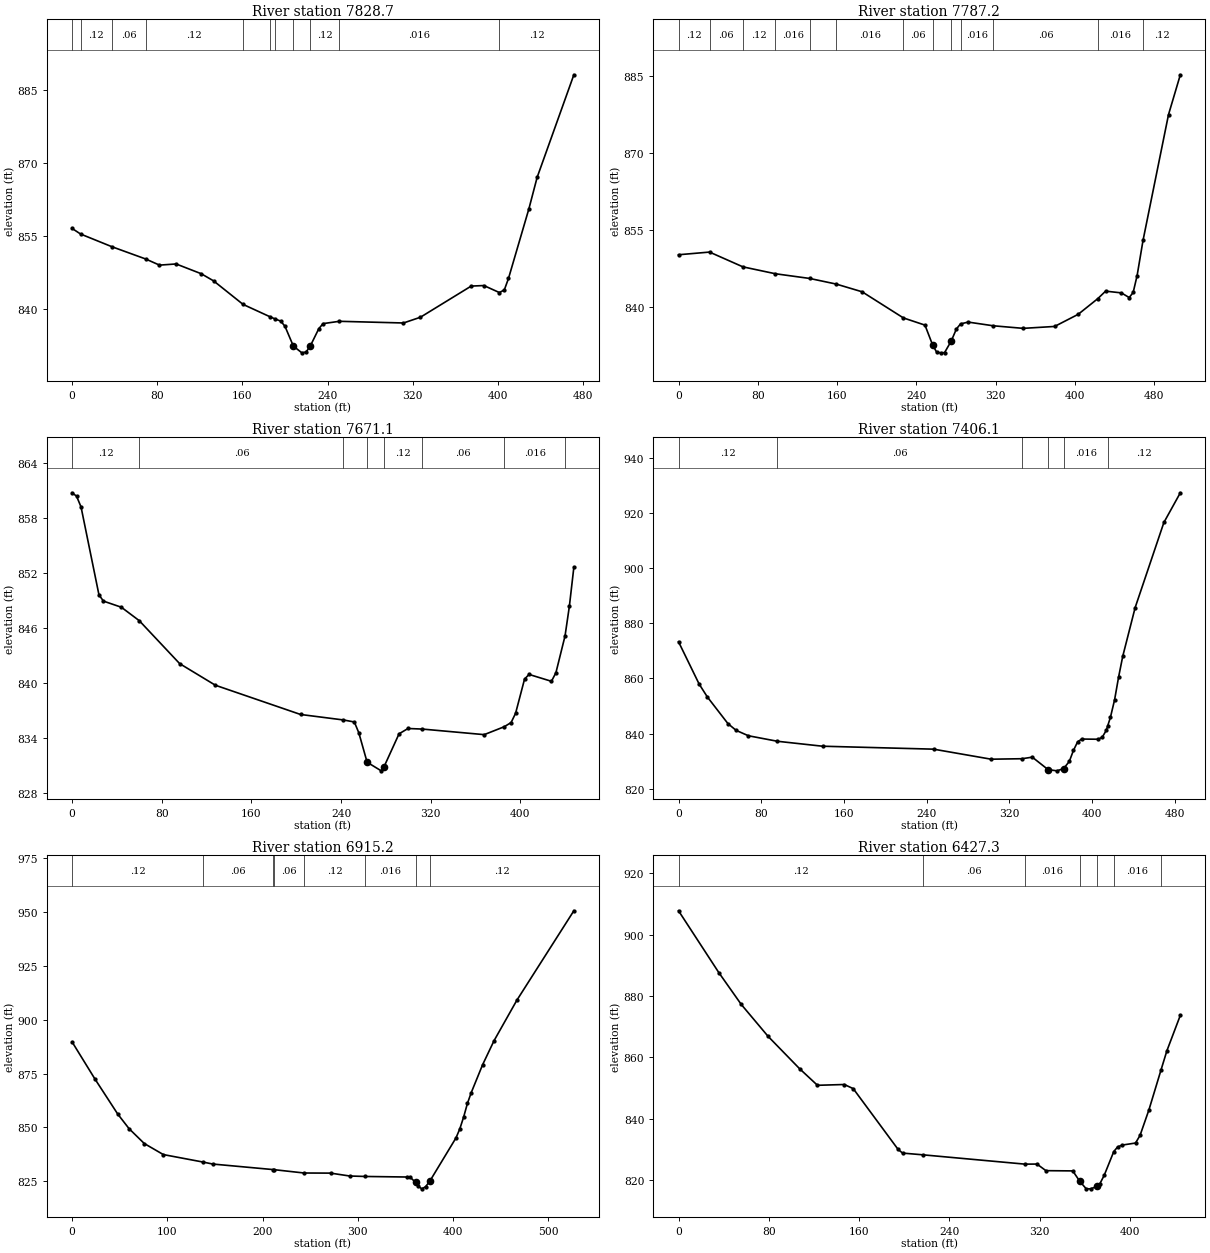
Type RM Length L Ch R = 1 ,7828.7  ,41.9,41.5,41.1
XS GIS Cut Line= 4
     1724222.713      362017.421     1724265.041      361854.745
     1724223.264      361640.128     1724233.534      361556.256
#Sta/Elev= 30
       0   856.6       8855.4454   37.64852.8161   69.04850.3199    82.1  849.05
    97.7  849.29   121.2  847.29   132.9  845.81  160.59840.9706  185.47838.4698
  190.79837.9653   195.9  837.54   199.9  836.48   207.8   832.4   215.8  831.01
   219.8  831.18   223.8  832.46   231.7  835.98   235.7  837.02  250.97837.4963
   311.2  837.15   327.1  838.33   374.8  844.74   386.7  844.85  401.25843.4106
   405.9  843.95   409.8   846.3     429  860.65   436.7  867.09   471.2   888.2
#Mann= 11 ,-1 , 0
       0     .06       0       8     .12       0   37.64     .06       0
   69.04     .12       0  160.59    .016       0  185.47     .06       0
  190.79     .12       0   207.8    .045       0   223.8     .12       0
  250.97    .016       0  401.25     .12       0
Bank Sta=207.8,223.8
XS Rating Curve= 0 ,0
Exp/Cntr=0.3,0.1

Type RM Length L Ch R = 1 ,7787.2  ,124.1,116.1,108.3
XS GIS Cut Line= 3
     1724397.419      362037.091     1724315.822        361888.6
     1724243.938      361559.431
#Sta/Elev= 30
       0  850.13   31.28850.6501   64.98847.7708   97.78846.4266  132.38845.5105
  159.11844.4174   185.3  842.91  226.89837.8257   248.7  836.42   256.6  832.46
   260.6  831.12   264.6  831.02   268.5  831.07   275.2  833.32   280.4  835.66
  284.59836.6571   292.3  837.01  317.58836.2919   347.8  835.79   379.5  836.16
   403.3  838.52  423.05841.5698     431  843.04   446.9   842.7   454.8  841.79
   458.8  842.78   462.8  846.08  468.74852.9095   494.5  877.45   506.4  885.19
#Mann= 13 ,-1 , 0
       0     .12       0   31.28     .06       0   64.98     .12       0
   97.78    .016       0  132.38     .06       0  159.11    .016       0
  226.89     .06       0   256.6    .045       0   275.2     .12       0
  284.59    .016       0  317.58     .06       0  423.05    .016       0
  468.74     .12       0
Bank Sta=256.6,275.2
XS Rating Curve= 0 ,0
Exp/Cntr=0.3,0.1

Type RM Length L Ch R = 1 ,7671.1  ,263.5,265,264
XS GIS Cut Line= 2
      1724530.64      361947.077     1724286.988      361571.403
#Sta/Elev= 30
       0  860.72       4  860.35       8  859.18      24  849.58      28   848.9
      44  848.23   59.97846.7642      96  842.08   127.9  839.72   203.9  836.53
  242.22  835.93   251.9  835.71   255.9  834.53   263.3  831.32   275.9  830.38
   278.3   830.8   291.8  834.42   299.8     835  312.62834.9372   367.8  834.33
  385.66835.1916   391.8  835.65   395.8  836.66   403.8  840.39   407.8   840.9
   427.8  840.15   431.8  841.09  439.94845.1072   443.8  848.34   447.8   852.6
#Mann= 8 ,-1 , 0
       0     .12       0   59.97     .06       0  242.22     .12       0
   263.3    .045       0   278.3     .12       0  312.62     .06       0
  385.66    .016       0  439.94     .12       0
Bank Sta=263.3,278.3
XS Rating Curve= 0 ,0
Exp/Cntr=0.3,0.1

Type RM Length L Ch R = 1 ,7406.1  ,481.4,490.8,495.3
XS GIS Cut Line= 2
     1724728.252      361813.555     1724458.989      361409.656
#Sta/Elev= 30
       0   873.3    19.9  857.99    27.8  853.33    47.8  843.62    55.7  841.18
    67.6  839.22   95.62837.2237   139.3  835.43   246.7  834.36   302.4  830.72
  332.25830.8945   342.2  831.46   357.5  826.94   366.1   826.5   372.5  827.33
     378  829.91     382   833.9     386  836.98   389.9  838.03   405.8  837.96
   409.8  838.65   413.8  841.21  415.12842.7676   417.8  845.93   421.8  852.23
   425.7  860.54   429.7  868.04   441.7   885.7   469.5  916.57   485.4  927.34
#Mann= 6 ,-1 , 0
       0     .12       0   95.62     .06       0  332.25     .12       0
   357.5    .045       0   372.5    .016       0  415.12     .12       0
Bank Sta=357.5,372.5
XS Rating Curve= 0 ,0
Exp/Cntr=0.3,0.1

Type RM Length L Ch R = 1 ,6915.2  ,482.6,487.9,492
XS GIS Cut Line= 2
     1725024.709      361613.246     1724817.054      361129.214
#Sta/Elev= 30
       0  889.73    23.9  872.55    47.9   856.2    59.8   849.4    75.8  842.48
    95.8  837.34  137.36833.8713   147.6  832.94  211.42830.3448  212.28830.3088
  243.56828.7716   271.3  828.72   291.3  827.38  307.84 827.162   351.1  826.91
   355.1   826.7   360.6   824.4   363.1  822.76   367.1  821.41   371.1  822.41
   375.6  825.05     403  845.11     407  849.31     411  854.78     415  861.15
     419  866.16   430.9  879.09   442.9  890.27   466.8  909.05   526.7  950.69
#Mann= 8 ,-1 , 0
       0     .12       0  137.36     .06       0  211.42     .12       0
  212.28     .06       0  243.56     .12       0  307.84    .016       0
   360.6    .045       0   375.6     .12       0
Bank Sta=360.6,375.6
XS Rating Curve= 0 ,0
Exp/Cntr=0.3,0.1

Type RM Length L Ch R = 1 ,6427.3  ,610.8,598.4,585
XS GIS Cut Line= 2
     1725401.396      361453.887     1725313.276      361018.121
#Sta/Elev= 30
       0  907.82    35.7  887.65    55.6  877.26    79.4  866.84   107.2  856.33
   123.1   850.9   146.9  851.16   154.8  849.81   194.5  830.01   198.5  828.79
  216.46828.2266  306.86825.1885   317.6  825.21   325.5  823.06   349.3  822.98
   355.6  819.54   361.2  817.15   365.2  817.13   370.6  817.92   373.1  818.66
   377.1  821.49  385.63829.2803     389  830.78     393   831.4   404.9  832.07
   408.9  834.55   416.8  842.91  427.39855.7787   432.7  862.17   444.6  873.72
#Mann= 7 ,-1 , 0
       0     .12       0  216.46     .06       0  306.86    .016       0
   355.6    .045       0   370.6     .12       0  385.63    .016       0
  427.39     .12       0
Bank Sta=355.6,370.6
XS Rating Curve= 0 ,0
Exp/Cntr=0.3,0.1

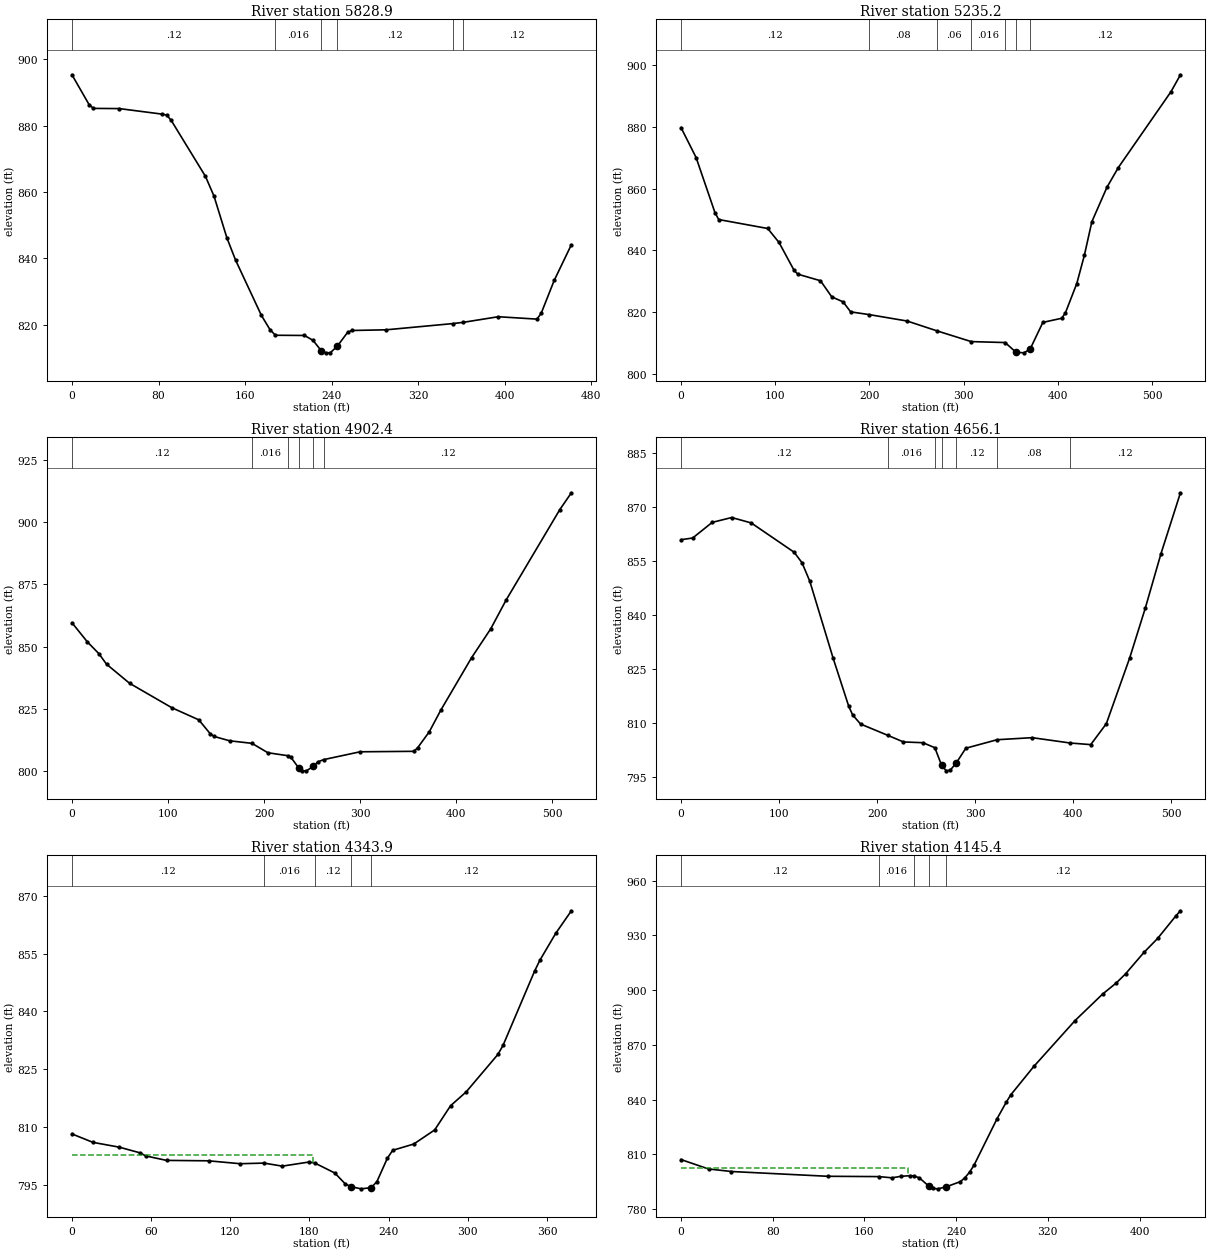
Type RM Length L Ch R = 1 ,5828.9  ,590.5,593.7,596.9
XS GIS Cut Line= 3
     1726043.664      361263.269     1725740.301      360936.777
     1725734.174      360922.072
#Sta/Elev= 30
       0  895.34    15.9  886.31    19.9   885.2    43.8  885.14    83.6  883.46
    87.5  883.16    91.5  881.71   123.4   864.7   131.3  858.73   143.2  846.16
   151.2  839.46   175.1  822.76     183  818.49  188.04816.7726   214.9  816.71
   222.8  815.24   230.3  812.16   234.8  811.47   238.8   811.5   245.3  813.49
   254.7  817.62   258.6  818.21   290.5  818.42  351.97820.2927  361.61820.6665
     394  822.36   429.8  821.64   433.7   823.4   445.7   833.3   461.6  844.09
#Mann= 6 ,-1 , 0
       0     .12       0  188.04    .016       0   230.3    .045       0
   245.3     .12       0  351.97     .06       0  361.61     .12       0
Bank Sta=230.3,245.3
XS Rating Curve= 0 ,0
Exp/Cntr=0.3,0.1

Type RM Length L Ch R = 1 ,5235.2  ,333.3,332.9,331
XS GIS Cut Line= 3
     1726488.182      360992.206     1726190.822      360565.683
     1726185.253       360557.37
#Sta/Elev= 30
       0   879.8      16  870.11      36  852.28      40  850.02      92  847.12
     104   842.6     120  833.56     124  832.32     148   830.2     160  824.97
     172  823.36     180  820.12  199.95819.2198     240  817.15  271.95813.9337
  307.96 810.492  343.97810.1818   355.5  807.03     364  806.85   370.5  808.08
     384  816.71     404  818.05     408  819.85     420   829.3     428  838.38
     436  849.32     452  860.46     464  866.82     520  891.44     530   896.9
#Mann= 7 ,-1 , 0
       0     .12       0  199.95     .08       0  271.95     .06       0
  307.96    .016       0  343.97     .12       0   355.5    .045       0
   370.5     .12       0
Bank Sta=355.5,370.5
XS Rating Curve= 0 ,0
Exp/Cntr=0.3,0.1

Type RM Length L Ch R = 1 ,4902.4  ,246.4,246.3,246.5
XS GIS Cut Line= 2
     1726751.328      360828.945     1726434.259      360417.009
#Sta/Elev= 30
       0  859.57      16  851.88      28  847.13      36  842.89      60   835.2
     104  825.37     132  820.51     144  814.88     148  813.83     164  812.09
  187.33811.0599   203.9  807.28   224.6806.0917   227.9  805.44   236.3     801
   239.9  800.01   243.9     800   251.3  801.79   255.9   803.6  261.87804.5031
   299.9  807.66   355.9  807.85   359.9  809.34   371.9   815.7   383.9  824.41
   415.9  845.48   435.9  857.14   451.8  868.64   507.8  905.08   519.8  911.82
#Mann= 6 ,-1 , 0
       0     .12       0  187.33    .016       0   224.6     .08       0
   236.3    .045       0   251.3     .08       0  261.87     .12       0
Bank Sta=236.3,251.3
XS Rating Curve= 0 ,0
Exp/Cntr=0.3,0.1

Type RM Length L Ch R = 1 ,4656.1  ,312.9,312.2,311.1
XS GIS Cut Line= 2
     1726959.612      360699.722     1726648.886      360296.028
#Sta/Elev= 30
       0  860.87    11.9  861.34    31.8  865.68    51.7  867.03    71.6  865.53
   115.4  857.39   123.4  854.48   131.3  849.39   155.2  827.94   171.1   814.6
   175.1  812.21   183.1   809.7  210.62806.5873   226.9  804.72   246.8  804.51
  258.89803.1122   265.8  798.24   270.6   796.7   274.6  796.88   280.8  798.91
   290.5  802.98  322.43 805.342   358.2  805.91  396.97804.4244   417.9  803.98
   433.8  809.79   457.7   828.1   473.6  841.92   489.5  856.96   509.4   873.9
#Mann= 7 ,-1 , 0
       0     .12       0  210.62    .016       0  258.89     .12       0
   265.8    .045       0   280.8     .12       0  322.43     .08       0
  396.97     .12       0
Bank Sta=265.8,280.8
XS Rating Curve= 0 ,0
Exp/Cntr=0.3,0.1

Type RM Length L Ch R = 1 ,4343.9  ,187.8,198.6,209.3
XS GIS Cut Line= 2
     1727155.487       360437.92     1726913.327      360146.965
#Sta/Elev= 30
       0  808.23    15.9  806.04    35.9  804.79    51.8   803.3    55.8  802.53
    71.7  801.36   103.6  801.25   127.5   800.5  145.54800.6593   159.4  799.87
   179.3  800.92  183.96800.6893   199.2  798.09   207.2  795.24   211.8  794.51
   219.2  793.98   226.8  794.29   231.1  795.84   239.1  801.97   243.1  803.98
     259   805.6   274.9  809.26   286.9  815.53   298.8  819.15   322.8  828.85
   326.7   831.2   350.6  850.46   354.6  853.28   366.6  860.26   378.5  866.13
#Mann= 5 ,-1 , 0
       0     .12       0  145.54    .016       0  183.96     .12       0
   211.8    .045       0   226.8     .12       0
#XS Ineff= 2 , 0
          182.37  802.76
Permanent Ineff=
       F       F
Bank Sta=211.8,226.8
XS Rating Curve= 0 ,0
Exp/Cntr=0.3,0.1

Type RM Length L Ch R = 1 ,4145.4  ,299.1,293.9,288.4
XS GIS Cut Line= 2
     1727254.111      360435.573     1727157.486      360010.684
#Sta/Elev= 30
       0  807.16      24  802.01      44  800.62   127.9     798   172.9 797.825
   183.9  797.16   191.9  797.97   199.9  798.36  203.18 798.196   207.9  797.16
   216.2   792.6   219.9  791.34   223.9  791.12   231.2  792.17   243.8   795.1
   247.8   797.3   251.8  800.31   255.8   804.3   275.8  829.66   283.8  838.67
   287.8  842.72   307.8  858.21   343.8  883.37   367.8  897.86   379.8  903.99
   387.8  908.94   403.8  920.65   415.8  928.35   431.7  940.71   435.7  943.51
#Mann= 5 ,-1 , 0
       0     .12       0   172.9    .016       0  203.18     .12       0
   216.2    .045       0   231.2     .12       0
#XS Ineff= 2 , 0
          198.36  802.73
Permanent Ineff=
       F       F
Bank Sta=216.2,231.2
XS Rating Curve= 0 ,0
Exp/Cntr=0.3,0.1

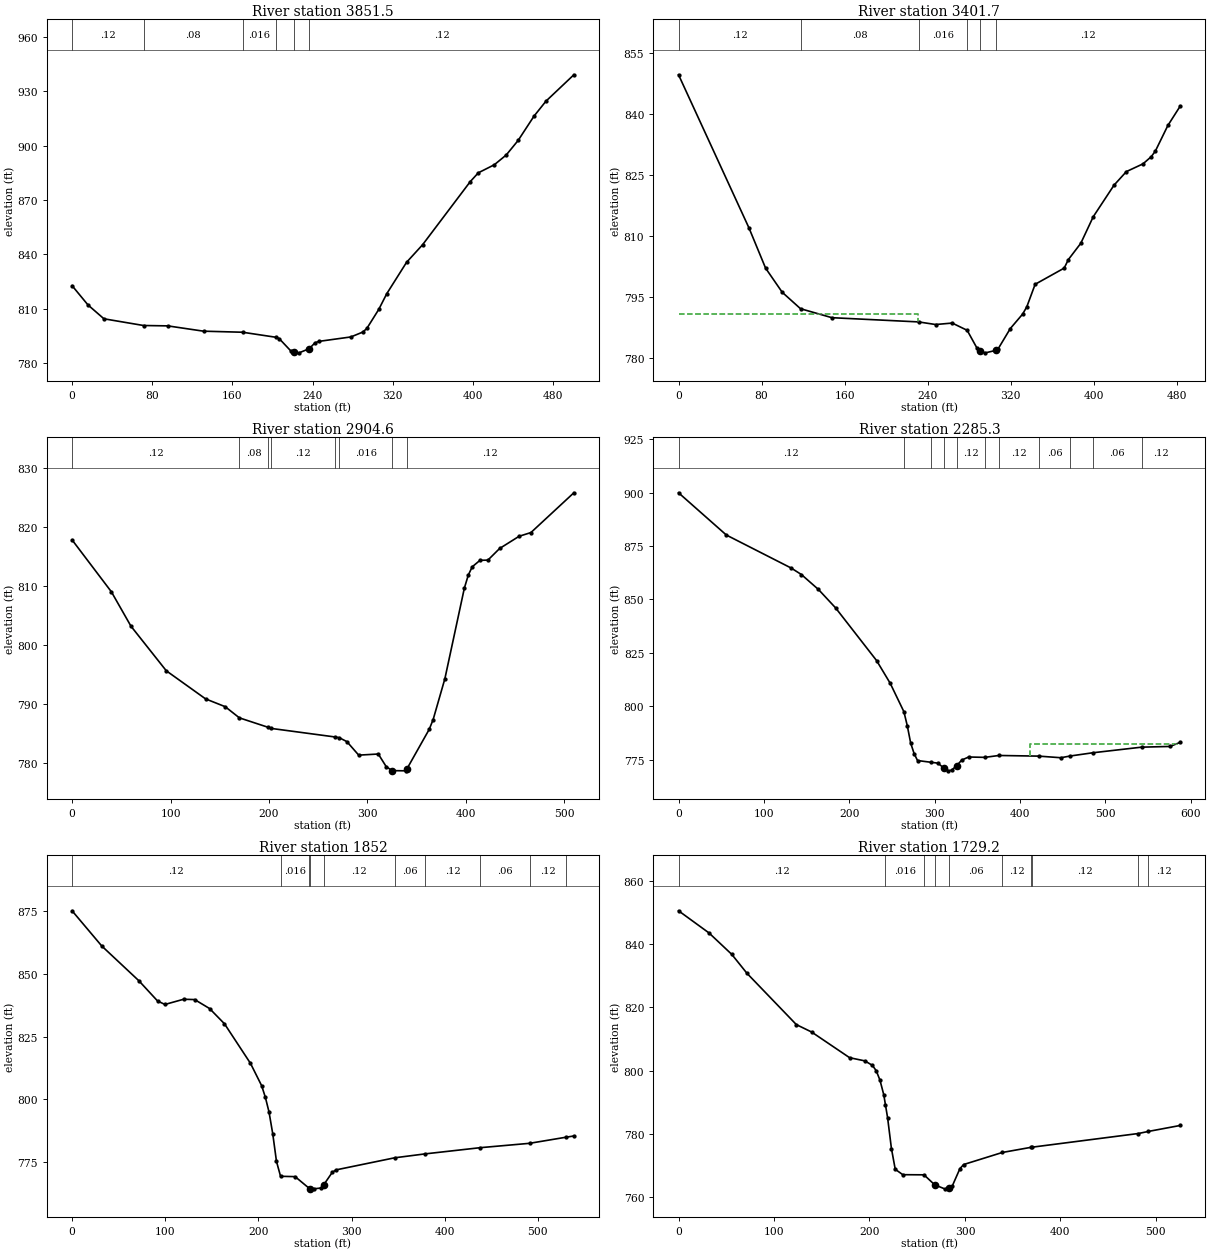
Type RM Length L Ch R = 1 ,3851.5  ,445.4,449.8,452.2
XS GIS Cut Line= 2
     1727589.503      360360.463     1727368.147      359911.309
#Sta/Elev= 30
       0  822.65    15.9  811.99    31.8  804.35   71.31800.6466    95.4  800.44
   131.2  797.51  170.09796.9299  203.01794.1864   206.6  793.45   218.6  786.41
   221.7   785.8   226.5  785.55   236.7  787.86   242.4   791.1   246.4  791.89
   278.2  794.33   290.1  797.02   294.1     799     306  809.51     314   818.2
   333.8  835.57   349.7  845.21   397.4  880.16   405.4  884.98   421.3  889.41
   433.2   894.8   445.1  902.85     461  916.32   472.9  924.56   500.7  939.11
#Mann= 6 ,-1 , 0
       0     .12       0   71.31     .08       0  170.09    .016       0
  203.01     .08       0   221.7    .045       0   236.7     .12       0
Bank Sta=221.7,236.7
XS Rating Curve= 0 ,0
Exp/Cntr=0.3,0.1

Type RM Length L Ch R = 1 ,3401.7  ,497.7,497,496
XS GIS Cut Line= 2
     1727955.863      360168.275     1727765.887      359723.684
#Sta/Elev= 30
       0  849.58    67.9  811.92    83.9  802.04    99.9  796.12  117.52792.0789
   147.8  789.87  231.36788.8309   247.7  788.19   263.7  788.55  278.11786.7658
   287.7  782.33   290.8  781.58   295.7  781.23   305.8  781.84   307.7  782.11
   319.7  787.21   331.6  790.77   335.6  792.56   343.6  798.08   371.6  802.06
   375.6  804.15   387.6  808.16   399.6  814.69   419.6  822.44   431.5  825.78
   447.5  827.68   455.5  829.45   459.5  830.85   471.5  837.12   483.5  841.92
#Mann= 6 ,-1 , 0
       0     .12       0  117.52     .08       0  231.36    .016       0
  278.11     .12       0   290.8    .045       0   305.8     .12       0
#XS Ineff= 2 , 0
          230.48   790.8
Permanent Ineff=
       F       F
Bank Sta=290.8,305.8
XS Rating Curve= 0 ,0
Exp/Cntr=0.3,0.1

Type RM Length L Ch R = 1 ,2904.6  ,617.7,619.3,618.7
XS GIS Cut Line= 3
     1728419.348      359978.859     1728286.812      359684.334
     1728206.514      359515.827
#Sta/Elev= 30
       0  817.76    39.9  808.97    59.8  803.14    95.7  795.58   135.6  790.82
   155.5   789.5  169.92787.6066  199.42785.9888  202.31785.8154  267.08784.3679
   271.4 784.242   279.1  783.58   291.1  781.29     311  781.48     319  779.35
   324.9  778.67   338.9  778.63   339.9  778.91   362.7  785.66   366.7  787.32
   378.6  794.23   398.4  809.59   402.4   811.8   406.4   813.2   414.3   814.3
   422.3  814.33   434.2   816.3     454  818.37     466     819   509.6  825.74
#Mann= 8 ,-1 , 0
       0     .12       0  169.92     .08       0  199.42     .06       0
  202.31     .12       0  267.08     .08       0   271.4    .016       0
   324.9    .045       0   339.9     .12       0
Bank Sta=324.9,339.9
XS Rating Curve= 0 ,0
Exp/Cntr=0.3,0.1

Type RM Length L Ch R = 1 ,2285.3  ,430.6,433.3,437.4
XS GIS Cut Line= 2
      1728972.32      359804.969     1728764.473      359255.242
#Sta/Elev= 30
       0  899.87      56  880.11   131.9  864.67   143.9  861.63   163.9  854.63
   183.9  846.05   231.9  821.42   247.9  810.77  263.96797.4507   267.9  790.93
   271.9  782.77   275.9   777.9   279.9  774.63  295.54773.8252   303.8  773.41
   310.8  771.07   315.8  769.81   319.8   770.1   325.8  772.28   331.8  774.88
   339.8  776.28  358.69776.1156  375.28776.9957  421.84776.6933   447.8  775.94
   458.8776.7525  484.99778.2503  542.32780.8848   575.7  781.22   587.7  783.16
#Mann= 11 ,-1 , 0
       0     .12       0  263.96    .016       0  295.54     .12       0
   310.8    .045       0   325.8     .12       0  358.69     .06       0
  375.28     .12       0  421.84     .06       0   458.8     .12       0
  484.99     .06       0  542.32     .12       0
#XS Ineff= 2 , 0
                          411.84          782.32
Permanent Ineff=
       F       F
Bank Sta=310.8,325.8
XS Rating Curve= 0 ,0
Exp/Cntr=0.3,0.1

Type RM Length L Ch R = 1 ,1852    ,122.8,122.8,122.8
XS GIS Cut Line= 2
     1729352.742      359685.339     1729211.039      359165.728
#Sta/Elev= 30
       0   875.1    31.9  861.07    71.8  847.21    91.8  839.18    99.7  837.81
   119.7  839.88   131.6  839.75   147.6  836.18   163.6  830.11   191.5  814.36
   203.5  805.46   207.5  800.81   211.4     795   215.4  786.31   219.4  775.34
  223.78769.3997   239.4  769.27  254.39 764.657     255  764.53   259.3  764.41
   267.3  764.74     270  765.96   279.3  770.98   283.3  771.95  346.23776.7643
  378.76778.3176  438.07780.7925  491.03782.5297  529.91784.9434   538.6  785.45
#Mann= 10 ,-1 , 0
       0     .12       0  223.78    .016       0  254.39     .12       0
     255    .045       0     270     .12       0  346.23     .06       0
  378.76     .12       0  438.07     .06       0  491.03     .12       0
  529.91     .06       0
Bank Sta=255,270
XS Rating Curve= 0 ,0
Exp/Cntr=0.3,0.1

Type RM Length L Ch R = 1 ,1729.2  ,50.8,50.9,50.8
XS GIS Cut Line= 2
     1729468.413      359648.965     1729330.121      359141.858
#Sta/Elev= 30
       0  850.58    31.9  843.57    55.8  836.77    71.7  830.78   123.4  814.55
   139.4   812.2   179.2  804.07   195.1  803.07   203.1  801.64   207.1  799.93
     211  796.95     215  792.32  216.69789.2358     219  785.02     223  775.31
     227  768.74   234.9  767.04   257.1766.9952   268.3  763.84   278.7  762.56
   283.3  762.69   286.7  763.44   294.7  768.93   298.6  770.25  339.15774.0717
  369.37775.7098  369.76775.7225  481.65780.0744  492.22780.7375   525.6  782.63
#Mann= 10 ,-1 , 0
       0     .12       0  216.69    .016       0   257.1     .12       0
   268.3    .045       0   283.3     .06       0  339.15     .12       0
  369.37     .06       0  369.76     .12       0  481.65     .06       0
  492.22     .12       0
Bank Sta=268.3,283.3
XS Rating Curve= 0 ,0
Exp/Cntr=0.3,0.1

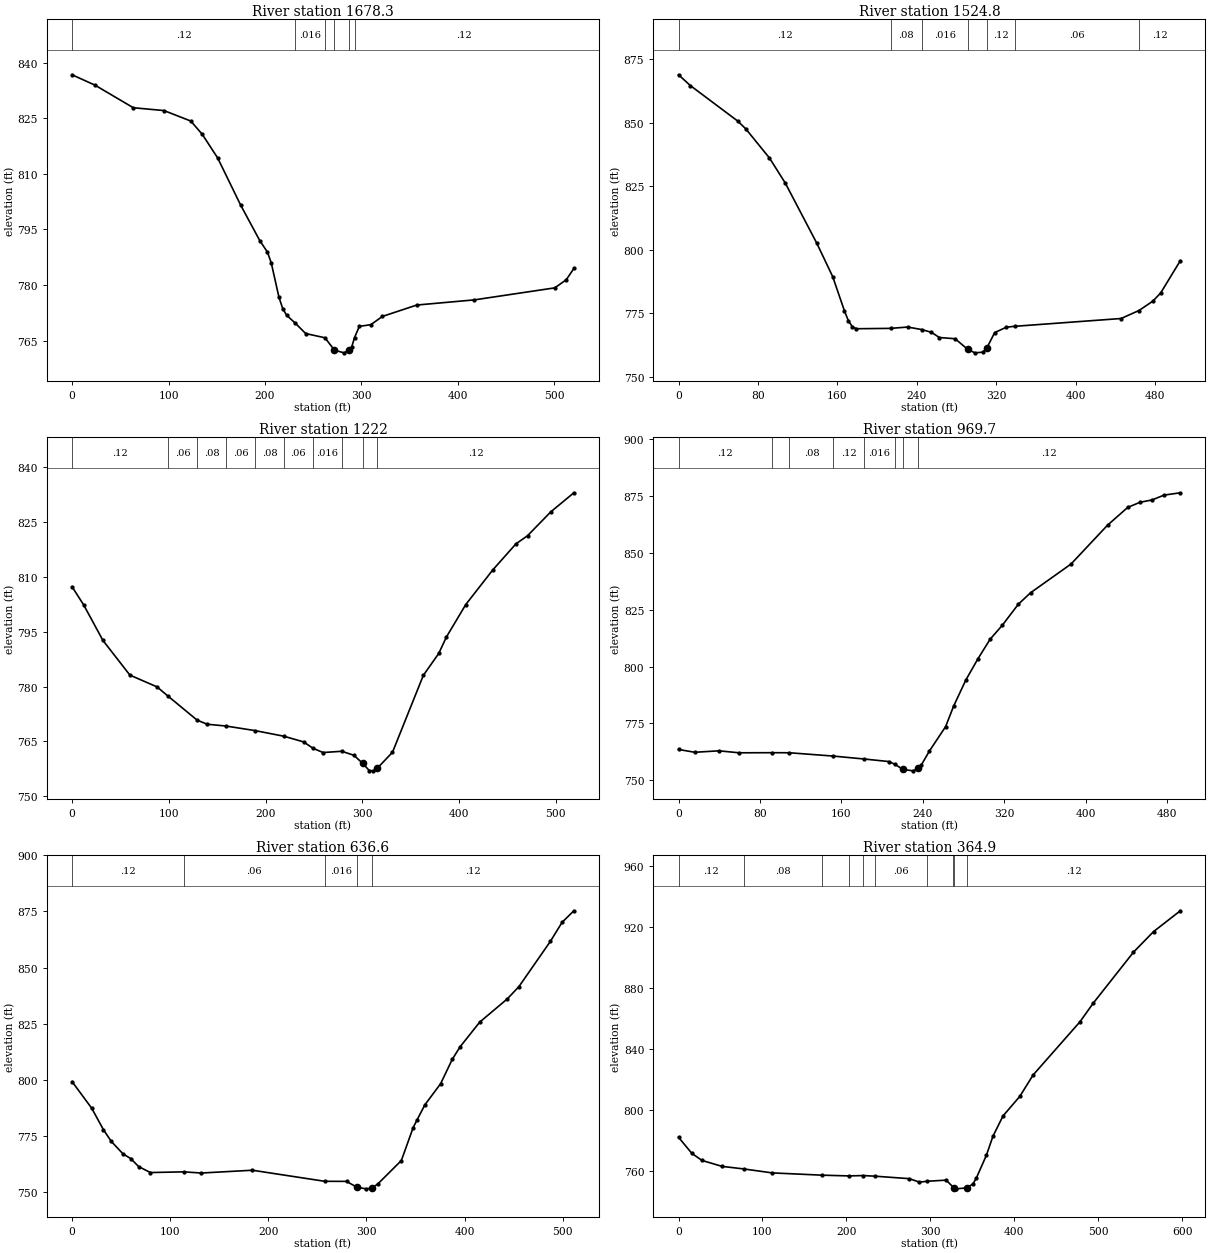
Type RM Length L Ch R = 1 ,1678.3  ,155.1,153.5,151.9
XS GIS Cut Line= 2
     1729516.637        359633.8     1729379.766      359131.907
#Sta/Elev= 30
       0  836.72    23.8  833.92    63.5  827.83    95.3  827.07   123.1  824.24
     135  820.65   150.9  814.31   174.7  801.61   194.6     792   202.5  788.93
   206.5     786   214.4  776.81   218.4  773.65   222.4  771.89  231.59 769.691
   242.2  766.94   262.2765.8008     272  762.46     282  761.74     287  762.39
   289.9  763.33  292.82765.8485   297.8  768.87   309.8  769.34   321.7  771.56
   357.4  774.63     417  776.02   500.4  779.26   512.3  781.44   520.2  784.49
#Mann= 6 ,-1 , 0
       0     .12       0  231.59    .016       0   262.2     .08       0
     272    .045       0     287     .08       0  292.82     .12       0
Bank Sta=272,287
XS Rating Curve= 0 ,0
Exp/Cntr=0.3,0.1

Type RM Length L Ch R = 1 ,1524.8  ,291.5,302.8,314.1
XS GIS Cut Line= 2
      1729679.95      359582.444       1729513.1       359105.18
#Sta/Elev= 30
       0  868.81    11.9  864.57    59.7  850.59    67.7  847.57    91.6  836.09
   107.5  826.28   139.3  802.58   155.3  789.46   167.2  775.94   171.2  772.02
   175.2  769.73   179.2  768.95  213.58769.0903   230.9  769.61  244.87768.6389
   254.8  767.54   262.8   765.5   278.7  765.01   291.4  760.82   298.6  759.47
   306.4  759.73   310.5  761.26   318.5  767.42   330.4  769.56  338.73769.9033
   445.9  772.97  463.88776.1021   477.7  779.74   485.7  782.95   505.6  795.72
#Mann= 7 ,-1 , 0
       0     .12       0  213.58     .08       0  244.87    .016       0
   291.4    .045       0   310.5     .12       0  338.73     .06       0
  463.88     .12       0
Bank Sta=291.4,310.5
XS Rating Curve= 0 ,0
Exp/Cntr=0.3,0.1

Type RM Length L Ch R = 1 ,1222    ,260.5,252.2,243.8
XS GIS Cut Line= 2
     1729823.253      359537.766     1729907.966      359026.029
#Sta/Elev= 30
       0  807.31      12  802.35    31.9  792.63    59.8  783.14    87.8  779.93
   99.21777.3919  129.15770.8535   139.6  769.71  159.08769.2186  189.02767.9726
  218.96766.4282   239.4  764.87   248.9763.1487   259.4  761.97  278.83762.3101
   291.3  761.22   300.5  758.98   307.2  757.04   311.2  756.96   315.5  757.67
   331.2  762.03   363.1  783.08     379  789.06     387  793.59     407  802.46
   434.9  811.92   458.8  819.04   470.8  821.27   494.8  827.79   518.7  833.02
#Mann= 10 ,-1 , 0
       0     .12       0   99.21     .06       0  129.15     .08       0
  159.08     .06       0  189.02     .08       0  218.96     .06       0
   248.9    .016       0  278.83     .12       0   300.5    .045       0
   315.5     .12       0
Bank Sta=300.5,315.5
XS Rating Curve= 0 ,0
Exp/Cntr=0.3,0.1

Type RM Length L Ch R = 1 ,969.7   ,335.9,333.1,330.4
XS GIS Cut Line= 2
     1730161.281       359470.64     1730061.137      358988.125
#Sta/Elev= 30
       0  763.53    15.9  762.29    39.7  762.93    59.6  762.06   91.75762.1082
  108.89762.0763  152.08760.6154  182.24759.3322   206.7   758.2  212.41757.0072
   220.6  754.71   230.5  754.12   235.6  755.26   238.4  756.67   246.4  762.86
   262.3  773.59   270.2  782.65   282.2  794.14   294.1  803.49     306  812.05
   317.9  818.16   333.8  827.51   345.8  832.53   385.5  845.17   421.3  862.25
   441.1  870.07   453.1  872.32     465  873.37   476.9   875.5   492.8  876.52
#Mann= 8 ,-1 , 0
       0     .12       0   91.75     .06       0  108.89     .08       0
  152.08     .12       0  182.24    .016       0  212.41     .12       0
   220.6    .045       0   235.6     .12       0
Bank Sta=220.6,235.6
XS Rating Curve= 0 ,0
Exp/Cntr=0.3,0.1

Type RM Length L Ch R = 1 ,636.6   ,256.5,271.7,286.7
XS GIS Cut Line= 2
     1730517.048      359399.991      1730353.14      358915.584
#Sta/Elev= 30
       0  799.24      20   787.4      32  777.81      40  772.62    51.9  767.08
    59.9  764.95    67.9   761.4    79.9  758.77  113.81759.0784   131.8  758.56
   183.8   759.8  257.55754.8745   279.7  754.84   290.2  752.26   299.6  751.52
   305.2  751.81   311.6  753.69   335.6  764.12   347.6  778.75   351.6  782.22
   359.6  788.93   375.6   798.3   387.5  809.17   395.5  814.76   415.5  825.73
   443.5  836.02   455.4  841.51   487.4   861.6   499.4  870.12   511.4  875.26
#Mann= 5 ,-1 , 0
       0     .12       0  113.81     .06       0  257.55    .016       0
   290.2    .045       0   305.2     .12       0
Bank Sta=290.2,305.2
XS Rating Curve= 0 ,0
Exp/Cntr=0.3,0.1

Type RM Length L Ch R = 1 ,364.9   ,147.5,149.8,151.5
XS GIS Cut Line= 2
     1730569.931      359395.184     1730763.843      358829.698
#Sta/Elev= 30
       0  782.13    15.9  771.56    27.9  766.97    51.8  763.06   77.67 761.381
   111.6  758.78  171.34757.2806  202.56756.8074  219.86757.0317  233.79 756.637
     275     755     287  752.71  296.23753.2997   318.8  754.03  327.46 749.322
   328.3  749.07   330.8  748.33   343.3  748.96   350.7  751.52   354.7  755.29
   366.7  770.24   374.6  782.85   386.6  796.17   406.5  808.89   422.4  822.97
   478.2  857.83   494.2  870.18     542   903.5   565.9  916.99   597.8  930.64
#Mann= 10 ,-1 , 0
       0     .12       0   77.67     .08       0  171.34     .06       0
  202.56     .12       0  219.86     .08       0  233.79     .06       0
  296.23    .016       0  327.46     .12       0   328.3    .045       0
   343.3     .12       0
Bank Sta=328.3,343.3
XS Rating Curve= 0 ,0
Exp/Cntr=0.3,0.1

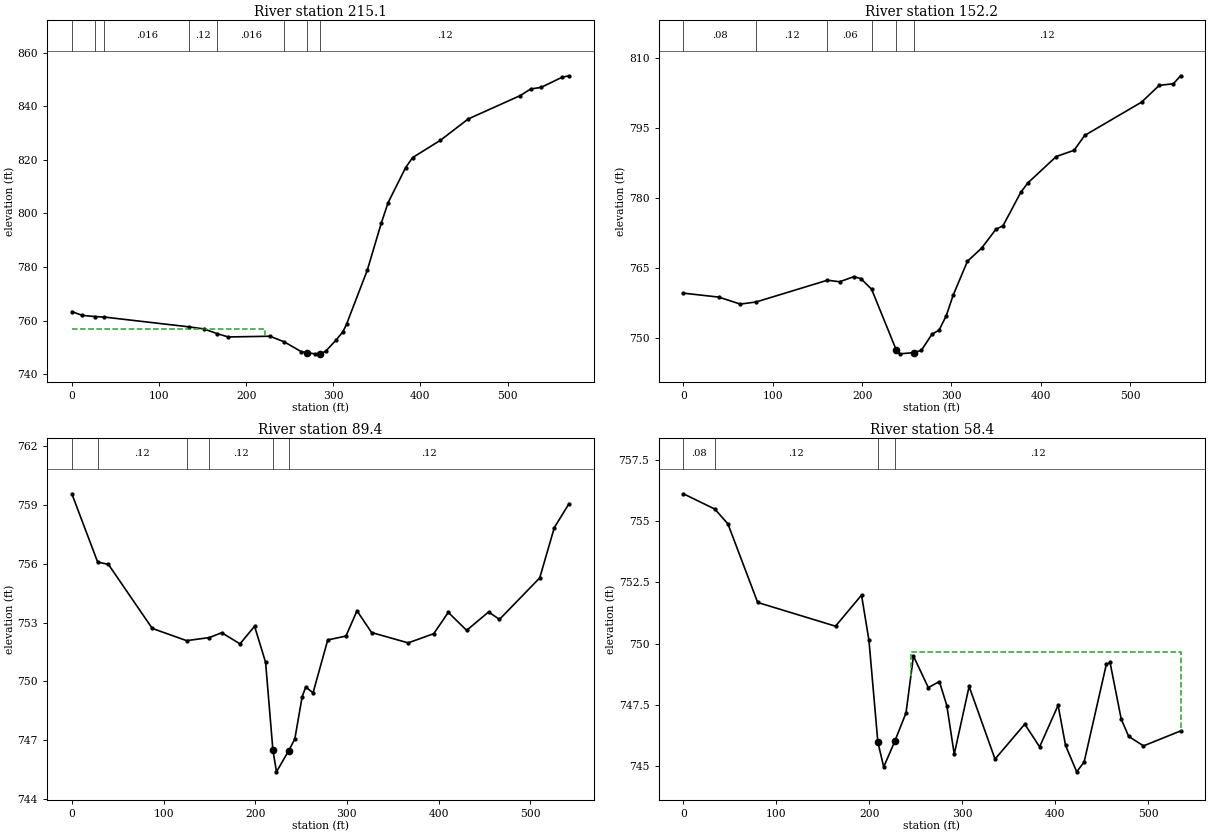
Type RM Length L Ch R = 1 ,215.1   ,63.1,62.9,63.1
XS GIS Cut Line= 2
     1730689.709      359415.015      1730921.96      358893.959
#Sta/Elev= 30
       0  763.36      12  761.95   26.08761.5255   37.48761.3121  134.49757.6671
   151.6  756.89  166.83755.1285   179.5   753.9   227.4  754.17   243.7 752.077
   263.3  748.42   270.3  747.98   279.2   747.6   285.3  747.66   291.2  748.52
   303.2  752.73   311.2  755.89   315.2  758.63   339.1  778.86     355  796.26
     363  804.06     383  817.06     391  820.82   422.9  827.27   454.8  835.23
   514.6  843.97   526.6  846.44   538.6  847.03   562.5   850.8   570.5  851.36
#Mann= 8 ,-1 , 0
       0    .016       0   26.08     .08       0   37.48    .016       0
  134.49     .12       0  166.83    .016       0   243.7     .12       0
   270.3    .045       0   285.3     .12       0
#XS Ineff= 2 , 0
          221.41  756.99
Permanent Ineff=
       F       F
Bank Sta=270.3,285.3
XS Rating Curve= 0 ,0
Exp/Cntr=0.3,0.1

Type RM Length L Ch R = 1 ,152.2   ,62.8,62.8,62.9
XS GIS Cut Line= 2
     1730752.845      359425.468     1730979.358      358917.287
#Sta/Elev= 30
       0  759.63    39.7  758.78    63.6  757.29   81.26757.7388  161.18762.3994
   174.9  762.07   190.8  763.16   198.7  762.73  210.61760.4649   238.4  747.38
   242.4  746.64   258.2  746.91   266.3  747.38   278.2  750.85   286.1   751.7
   294.1  754.77     302  759.25   317.9  766.46   333.8  769.28   349.7  773.29
   357.7  774.06   377.5  781.18   385.5  783.23   417.3  788.88   437.2  790.21
   449.1  793.39   512.7  800.51   532.5   804.1   548.4  804.46   556.4  806.16
#Mann= 6 ,-1 , 0
       0     .08       0   81.26     .12       0  161.18     .06       0
  210.61     .12       0   238.4    .045       0   258.2     .12       0
Bank Sta=238.4,258.2
XS Rating Curve= 0 ,0
Exp/Cntr=0.3,0.1

Type RM Length L Ch R = 1 ,89.4    ,31.1,31.1,31.1
XS GIS Cut Line= 2
     1730816.432      359435.996     1731037.165      358940.781
#Sta/Elev= 30
       0  759.58   28.12756.0934    39.9  755.97    87.7   752.7  125.13 752.075
  150.09752.2318   163.4  752.48   183.4  751.91   199.3  752.81   211.3  750.97
   219.3  746.48   223.2  745.37   236.4  746.44   243.2  747.05   251.2  749.21
   255.1   749.7   263.1  749.41   279.1  752.11     299  752.31     311   753.6
   326.9  752.49   366.8  751.96   394.7  752.43   410.6  753.52   430.6   752.6
   454.5  753.54   466.4  753.16   510.3  755.28   526.2  757.85   542.2  759.07
#Mann= 6 ,-1 , 0
       0     .08       0   28.12     .12       0  125.13     .06       0
  150.09     .12       0   219.3    .045       0   236.4     .12       0
Bank Sta=219.3,236.4
XS Rating Curve= 0 ,0
Exp/Cntr=0.3,0.1

Type RM Length L Ch R = 1 ,58.4    ,62.1,58.4,54.6
XS GIS Cut Line= 2
      1730848.11       359441.24     1731065.964      358952.485
#Sta/Elev= 30
       0  756.12   33.86755.4932    47.9  754.89    79.9  751.68   163.7  750.71
   191.7  751.98   199.7  750.13  209.32  745.96   215.6  744.96   227.4     746
   239.6  747.17   247.6  749.49   263.6   748.2   275.5  748.45   283.5  747.47
   291.5  745.48   307.5  748.25   335.4  745.28   367.4  746.71   383.4  745.78
   403.3  747.48   411.3  745.84   423.3  744.76   431.3  745.16   455.2  749.15
   459.2  749.23   471.2  746.92   479.2  746.21   495.2  745.82   535.1  746.43
#Mann= 4 ,-1 , 0
       0     .08       0   33.86     .12       0  209.32    .045       0
   227.4     .12       0
#XS Ineff= 2 , 0
                          244.84          749.64
Permanent Ineff=
       F       F
Bank Sta=209.32,227.4
XS Rating Curve= 0 ,0
Exp/Cntr=0.3,0.1

Chan Stop Cuts=-1
Use User Specified Reach Order=0
Composite Channel Slope=5